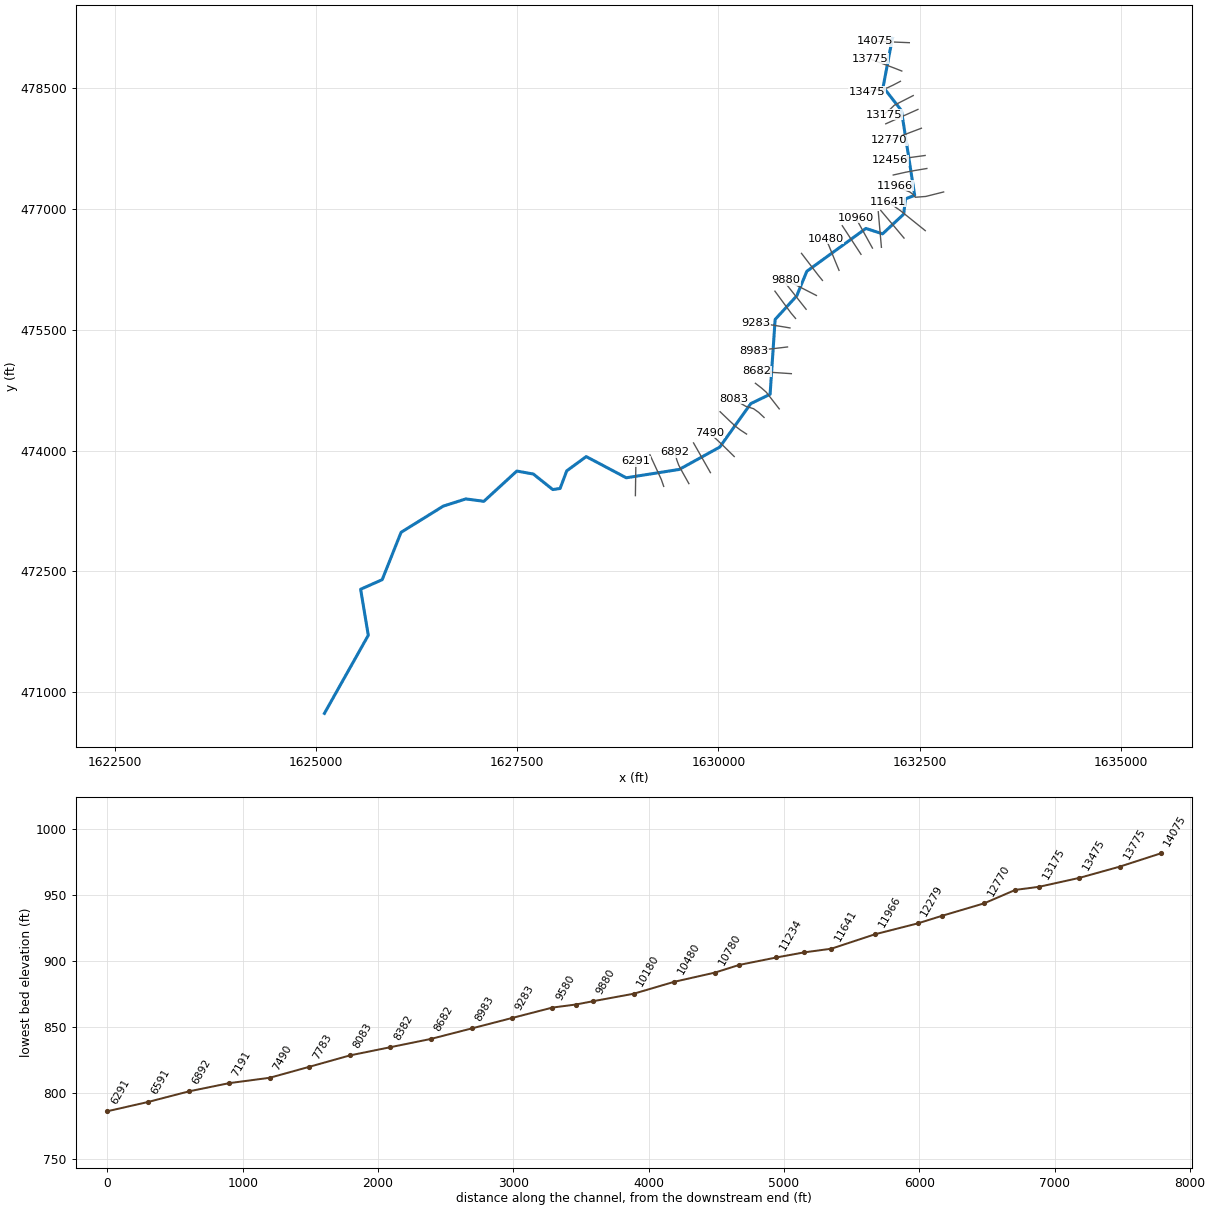
--- LwrBwmRn.prj (project) ---

Proj Title=LwrBwmRn
Current Plan=p01
Default Exp/Contr=0,0
English Units
Geom File=g01
Flow File=f01
Plan File=p01
BEGIN DESCRIPTION:
---------- MODELED AS PART OF WVEM CTP PROGRAM, 2025----------
Stream Name: Lower Bowman Run
Flood Zone: AFH
Marshall County, WV
HEC-RAS Version: RAS 6.6
Vertical Datum: NAVD88
Projection: NAD 1983 StatePlane West Virginia N FIPS 4701 (US Feet)
Terrain: 1-meter West Virginia FEMA R3 South Central (collected 2018-2019)
Land Use: 2024 NLCD
Hydrologic Method:
Duda et al., "Estimation of magnitude and frequency of floods for rural, unregulated streams in and near Virginia and West Virginia." September 8, 2025.
Additional Model Notes:
None
END DESCRIPTION:
DSS Export Rating Curves= 0
DSS Export Rating Curve Sorted= 0
DSS Export Volume Flow Curves= 0
DXF OffsetX= 0
DXF OffsetY= 0
DXF ScaleX= 0
DXF ScaleY= 0

--- LwrBwmRn.p01 (plan) ---

Plan Title=Floodplain
Program Version=6.60
Short Identifier=Floodplain
Geom File=g01
Flow File=f01
Subcritical Flow
K Sum by GR= 0
Std Step Tol= 0.01
Critical Tol= 0.01
Num of Std Step Trials= 20
Max Error Tol= 0.3
Flow Tol Ratio= 0.001
Split Flow NTrial= 30
Split Flow Tol= 0.02
Split Flow Ratio= 0.02
Log Output Level= 0
Friction Slope Method= 1
Unsteady Friction Slope Method= 2
Unsteady Bridges Friction Slope Method= 1
Parabolic Critical Depth
Global Vel Dist= 0 , 0 , 0
Global Log Level= 0
CheckData=False
Encroach Param=-1 ,0,0, 0
Flow Ratio Tolerance=0.1
Flow Ratio Min Ratio=0.5
Flow Ratio Max Ratio=4
Flow Ratio Max Iterations= 10
Mapping Interval=1HOUR
Computation Time Step Use Courant=        0
Computation Time Step Use Time Series=    0
Computation Time Step Count To Double=0
Computation Time Step Max Doubling=0
Computation Time Step Max Halving=0
Computation Time Step Residence Courant=0
Run HTab= 0
Run UNet= 0
Run Sediment= 0
Run PostProcess= 0
Run WQNet= 0
Run RASMapper=-1
UNET Theta= 0
UNET Theta Warmup= 0
UNET ZTol= 0
UNET ZSATol= 0
UNET MxIter= 0
UNET Max Iter WO Improvement= 0
UNET MaxInSteps= 0
UNET DtIC= 0
UNET DtMin= 0
UNET MaxCRTS= 0
UNET WFStab= 0
UNET SFStab= 0
UNET WFX= 1
UNET SFX= 1
UNET Gravity=32.17405
UNET 1D Methodology=Finite Difference
UNET DSS MLevel= 1
UNET Pardiso=0
UNET DZMax Abort= 0
UNET Use Existing IB Tables= 0
UNET Froude Reduction=False
UNET Froude Limit= 0
UNET Froude Power= 0
UNET D1 Cores= 0
UNET WindReference=Eulerian
UNET WindDragFormulation=Hsu (1988)
UNET D2 Coriolis=0
UNET D2 Cores= 0
UNET D2 Theta= 1
UNET D2 Theta Warmup= 1
UNET D2 Z Tol= 0.01
UNET D2 Volume Tol= 0.01
UNET D2 Max Iterations= 20
UNET D2 Advanced Convergence=0
UNET D2 WS Max Tol=0.15
UNET D2 WS RMS Tol=0.002
UNET D2 WS Stall Tol=1
UNET D2 Equation= 0
UNET D2 RampUpFraction=0.1
UNET D2 TimeSlices= 1
UNET D2 Turbulence Formulation=Non-Conservative (original)
UNET D2 Eddy Viscosity=0.3
UNET D2 Transverse Eddy Viscosity=0.1
UNET D2 Smagorinsky Mixing=0
UNET D2 BCVolumeCheck=0
UNET D2 Cores=0
UNET D2 SolverType=PARDISO (Direct)
UNET D2 Minimum Iterations= 3
UNET D2 Maximum Iterations= 30
UNET D2 Restart Number= 10
UNET D2 Relaxation Coeff=1.3
UNET D2 SOR Precondition Iterations= 10
UNET D2 ILUT Maximum Fill= 8
UNET D2 ILUT Tolerance=1E-08
UNET D2 Convergence Tolerance=0.00001
PS Theta= 1
PS WS Tol= 0.01
PS Volume Tol= 0.01
PS Max Iterations= 20
PS Equation= 0
PS Advance Time Step=-1
PS Target Courant=0.9
PS Time Slices= 1
PS Iterate With 2D=0
PS Project Initial WSE from DS=-1
PS Ramp Up Initial WSE from US=-1
PS Cores=0
UNET D1D2 MaxIter= 0
UNET D1D2 ZTol=0.01
UNET D1D2 QTol=0.1
UNET D1D2 MinQTol=1
Write IC File= 0
Write IC File at Fixed DateTime=0
Write IC File at Sim End=0
Echo Input=False
Echo Parameters=False
Echo Output=False
Write Detailed= 0
HDF Write Warmup=0
HDF Write Time Slices=0
HDF Flush=0
HDF Compression= 1
HDF Chunk Size= 1
HDF Spatial Parts= 1
HDF Use Max Rows=0
HDF Fixed Rows= 1
Calibration Method= 0
Calibration Iterations= 20
Calibration Max Change=0.05
Calibration Tolerance=0.2
Calibration Maximum=1.5
Calibration Minimum=0.5
Calibration Optimization Method= 1
WQ AD Non Conservative
WQ ULTIMATE=-1
WQ Max Comp Step=1HOUR
WQ Output Interval=15MIN
WQ Output Selected Increments= 0
WQ Create Restart=0
WQ Fixed Restart=0
WQ System Summary=0
WQ Write To DSS=0
Sorting and Armoring Iterations= 10
XS Update Threshold= 0.02
Bed Roughness Predictor= 0
Processes Affected by Predictor=Sediment Only
Hydraulics Update Threshold= 0.02
Energy Slope Method= 1
Volume Change Method= 1
Sediment Retention Method= 0
Sediment TS Multiplier= 1
Warm Up Method= 0
XS Weighting Method= 0
Number of US Weighted Cross Sections= 1
Number of DS Weighted Cross Sections= 1
Upstream XS Weight=0
Main XS Weight=1
Downstream XS Weight=0
Number of DS XS's Weighted with US Boundary= 1
Upstream Boundary Weight= 1
Weight of XSs Associated with US Boundary= 0
Number of US XS's Weighted with DS Boundary= 1
Downstream Boundary Weight= 0.5
Weight of XSs Associated with DS Boundary= 0.5
Percentile Method= 0
Sediment Output Level= 3
Mass or Volume Output= 0
Output Increment Type= 1
Profile and TS Output Increment= 1
Transport Output Increment 1
XS Output Flag= 0
XS Output Increment= 10
Read HDF5 Sediment Hotstart= 0
Sediment Hotstart Type= 0
Write Gradation File= 0
Read Gradation Hotstart= 0
Write HDF5 File= 1
Write Binary Output= 1
Write DSS Sediment File= 0
DSS Sediment Output Type= 1
SV Curve= 0
Specific Gage Flag= 0
Subcell Erosion Methods= 0
Subcell Deposition Methods= 0
Advection Scheme= 1
Matrix Solver= 0
Implicit Weighting Factor= 1
Maximum Outer Loop Convergence Iterations= 5
Convergence Maximum Absolute= 0.001
Convergence RMSE= 0.0001
Grain Fractions Max Abs Error= 0.001
Max Subgrid Regions= 1
Max Subgrid Length Scale= 3.402823E+38
Initial Layer Thickness= 3
Min Layer Thickness= 0.1
Max Layer Thickness= 6
Number of Layers= 5

--- LwrBwmRn.f01 (steady flow) ---

Flow Title=Flow
Program Version=6.60
Number of Profiles= 1
Profile Names=P100yr
River Rch & RM=LwrBwmRn,Main,14075
     725
River Rch & RM=LwrBwmRn,Main,11641
    1010
River Rch & RM=LwrBwmRn,Main,8682
    1280
River Rch & RM=LwrBwmRn,Main,2991
    1850
Boundary for River Rch & Prof#=LwrBwmRn,Main            , 1
Up Type= 0
Dn Type= 3
Dn Slope=0.00964
DSS Import GetInterval= 0
DSS Import GetPeak= 0
DSS Import FillOption= 0

--- LwrBwmRn.g01 (geometry) ---

Geom Title=Geometry
Program Version=6.60

River Reach=LwrBwmRn        ,Main
Reach XY= 30
     1632160.677      479122.276     1632045.714      478517.535
     1632272.847      478226.265     1632437.824      477171.626
     1632323.482      477127.257     1632301.318      476937.597
     1632039.279      476693.104     1631832.234      476760.213
     1631097.745      476227.265     1630973.178      475922.894
1630704.41914279475629.377499064     1630642.068       474699.49
1630401.69605143474583.472996049     1630016.768      474043.366
     1629513.886      473765.944      1628855.12      473662.021
     1628358.403      473925.351     1628116.209       473748.33
     1628033.423      473529.035      1627942.71      473515.824
     1627701.397      473708.698     1627496.193      473745.688
     1627086.666      473369.627     1626863.037       473399.43
     1626583.467      473310.3731626058.54798278472984.666018789
     1625823.736      472395.899     1625556.002      472276.673
     1625651.118      471705.096     1625106.213      470734.745

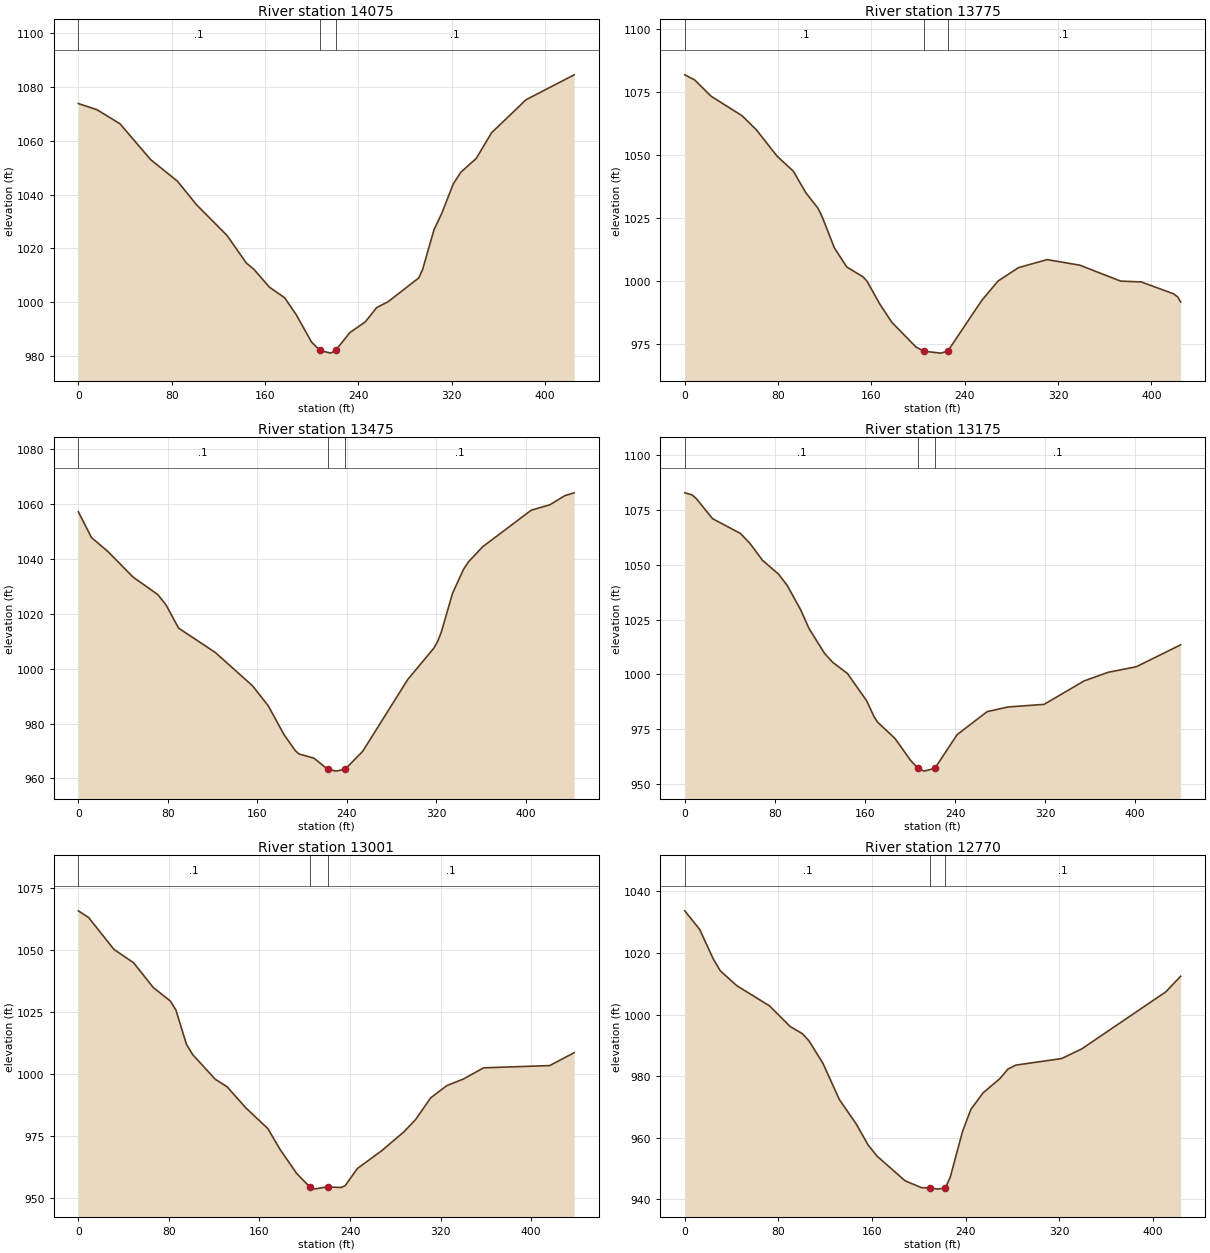
Type RM Length L Ch R = 1 ,14075   ,301.7,300,296.9
XS GIS Cut Line= 6
1632371.05861667479068.1776600931632283.62932959479071.898125082
  1632208.694112479075.020822257  1632108.780926479079.184855923
1632033.84603651479082.3068969251631946.43380976479086.026705757
#Sta/Elev= 30
       0 1073.72    15.9 1071.45    35.7 1066.22      62 1052.93    84.9 1044.96
   101.4 1036.17   127.6 1024.75     144  1014.6   150.6 1012.24   163.7 1005.69
   176.9 1001.71   186.7  995.51   199.9  985.32   207.2982.1894   216.3  981.21
   220.5982.1991   232.7   988.8     246  992.81   255.7  998.08   265.5 1000.26
   291.8 1009.08   295.1 1012.21   304.9 1026.98   311.5 1032.99   321.4 1043.94
   327.9 1048.28   341.1 1053.38   354.2 1062.89   383.8 1075.14     425 1084.36
#Mann= 3 ,-1,0
       0      .1       0   207.2    .045       0   220.5      .1       0
Bank Sta=207.2,220.5
XS Rating Curve= 0 ,0
Exp/Cntr(USF)=0,0
Exp/Cntr=0.3,0.1

Type RM Length L Ch R = 1 ,13775   ,295.5,300,305.5
XS GIS Cut Line= 6
1632277.67888217478716.1140597611632196.22596109478748.365307584
1632126.11258426478774.9945194271632032.54256143478810.274632588
1631962.36553642478836.7352095841631880.52908592478867.721696168
#Sta/Elev= 30
       0 1081.92     8.5 1079.88    22.6  1073.4    49.1 1065.65    61.4 1060.04
    79.1 1049.59    93.1 1043.59   103.7 1035.08   114.2 1028.87   117.7 1025.58
   128.2 1013.16   138.8 1005.54   152.8 1001.59   156.3  999.84   166.8  991.06
   177.4  983.57   198.4  973.61   205.3  972.01   219.4  971.26   225.4972.0062
   254.5  992.14   268.5  999.91     286 1005.24   310.6 1008.44   338.6 1006.24
   373.7  999.89   391.3  999.58   419.3   994.8   422.8  993.49   425.1  991.61
#Mann= 3 ,-1,0
       0      .1       0   205.3    .045       0   225.4      .1       0
Bank Sta=205.3,225.4
XS Rating Curve= 0 ,0
Exp/Cntr(USF)=0,0
Exp/Cntr=0.3,0.1

Type RM Length L Ch R = 1 ,13475   ,295.3,300,299.7
XS GIS Cut Line= 6
  1632260.583772478588.4148400871632171.40383226478541.700366586
1632099.02930509478507.3972855961632001.01637776 478487.56103918
1631927.50668226478472.6841004191631841.74537084478455.327507839
#Sta/Elev= 30
       0 1057.24    11.8 1047.83    26.6 1042.69    48.9 1033.44    71.1 1027.04
    78.5 1023.24    89.6 1014.84   122.5 1005.93   155.7  993.82   169.7  986.56
   183.9  975.99     194  970.13   197.3  968.94   210.7  967.39   222.8963.4109
   230.4  962.68   238.6963.4025   254.2  969.88   294.5  996.07   317.8 1007.49
   321.2 1009.94   324.5 1013.33   334.6 1027.56   344.5 1036.35   348.9 1039.03
   361.5 1044.48   404.9 1057.81   421.6 1059.79     435 1063.13   443.3 1064.15
#Mann= 3 ,-1,0
       0      .1       0   222.8    .045       0   238.6      .1       0
Bank Sta=222.8,238.6
XS Rating Curve= 0 ,0
Exp/Cntr(USF)=0,0
Exp/Cntr=0.3,0.1

Type RM Length L Ch R = 1 ,13175   ,173.7,174.1,173
XS GIS Cut Line= 6
1632419.78292868478411.0687380881632341.80637859478371.370654762
1632274.96924192478337.3444760891632185.85295033478291.976128504
1632129.59387651478237.5953317581632053.19901617478173.601037174
#Sta/Elev= 30
       0 1082.85     6.3 1081.96      10 1080.34    24.7 1071.05    49.4 1064.32
    57.9 1059.77    68.9 1052.13    83.3 1045.72      91 1040.59     103 1029.39
   110.3 1021.02   124.1 1009.61   131.5 1005.47   144.5 1000.41   161.6  987.92
   168.3  980.51   171.3   978.2   186.7  970.78   200.6  960.76   207.2957.1741
   212.5  955.88   222.1  957.16   241.9  972.53   268.6  983.03   287.2  985.16
   319.1  986.33   354.7  997.04   376.1 1000.98   401.1 1003.51   440.4  1013.5
#Mann= 3 ,-1,0
       0      .1       0   207.2    .045       0   222.1      .1       0
Bank Sta=207.2,222.1
XS Rating Curve= 0 ,0
Exp/Cntr(USF)=0,0
Exp/Cntr=0.3,0.1

Type RM Length L Ch R = 1 ,13001   ,230.8,230.8,229.4
XS GIS Cut Line= 2
1632478.35643253478239.2034079041632078.62232033478060.133805614
#Sta/Elev= 30
       0 1065.91     9.1 1063.21    31.5 1050.33    48.8 1044.95    66.3 1034.91
    81.3  1029.5    86.2 1025.87    95.5 1012.05     101 1007.88   120.9  997.95
   131.5  994.85   148.2  986.27   167.4  978.02   178.2   969.6   192.9  959.88
   204.5954.4642   207.8  953.57   220.2  954.48   232.1  954.23   235.7  954.96
   246.5  961.88   268.1  969.12   287.3  976.57     298  981.69   311.2  990.38
   325.6  995.39     340  997.98     358 1002.54   416.4 1003.44     438 1008.64
#Mann= 3 ,-1,0
       0      .1       0   204.5    .045       0   220.2      .1       0
Bank Sta=204.5,220.2
XS Rating Curve= 0 ,0
Exp/Cntr(USF)=0,0
Exp/Cntr=0.3,0.1

Type RM Length L Ch R = 1 ,12770   ,315.5,314.6,313
XS GIS Cut Line= 2
1632521.19732286478005.3726476911632125.08762152477855.418789144
#Sta/Elev= 30
       0 1033.64    12.7 1027.62    24.1 1018.21    30.3 1014.19    44.3 1009.39
    72.4  1002.8    89.9  996.15   100.5  993.77     106  991.51     118  984.18
     132  972.43   146.3  964.58   156.6  957.68   164.1  954.11   188.1  946.08
   202.2  943.82   209.2  943.77   216.2  943.36   222.6  943.79   226.7  947.19
   237.2  962.04   244.3  969.19   254.8  974.61   268.8   979.1   276.1  982.33
   282.8  983.59   321.9  985.72     339  988.84   410.8 1007.34   423.5 1012.42
#Mann= 3 ,-1,0
       0      .1       0   209.2    .045       0   222.6      .1       0
Bank Sta=209.2,222.6
XS Rating Curve= 0 ,0
Exp/Cntr(USF)=0,0
Exp/Cntr=0.3,0.1

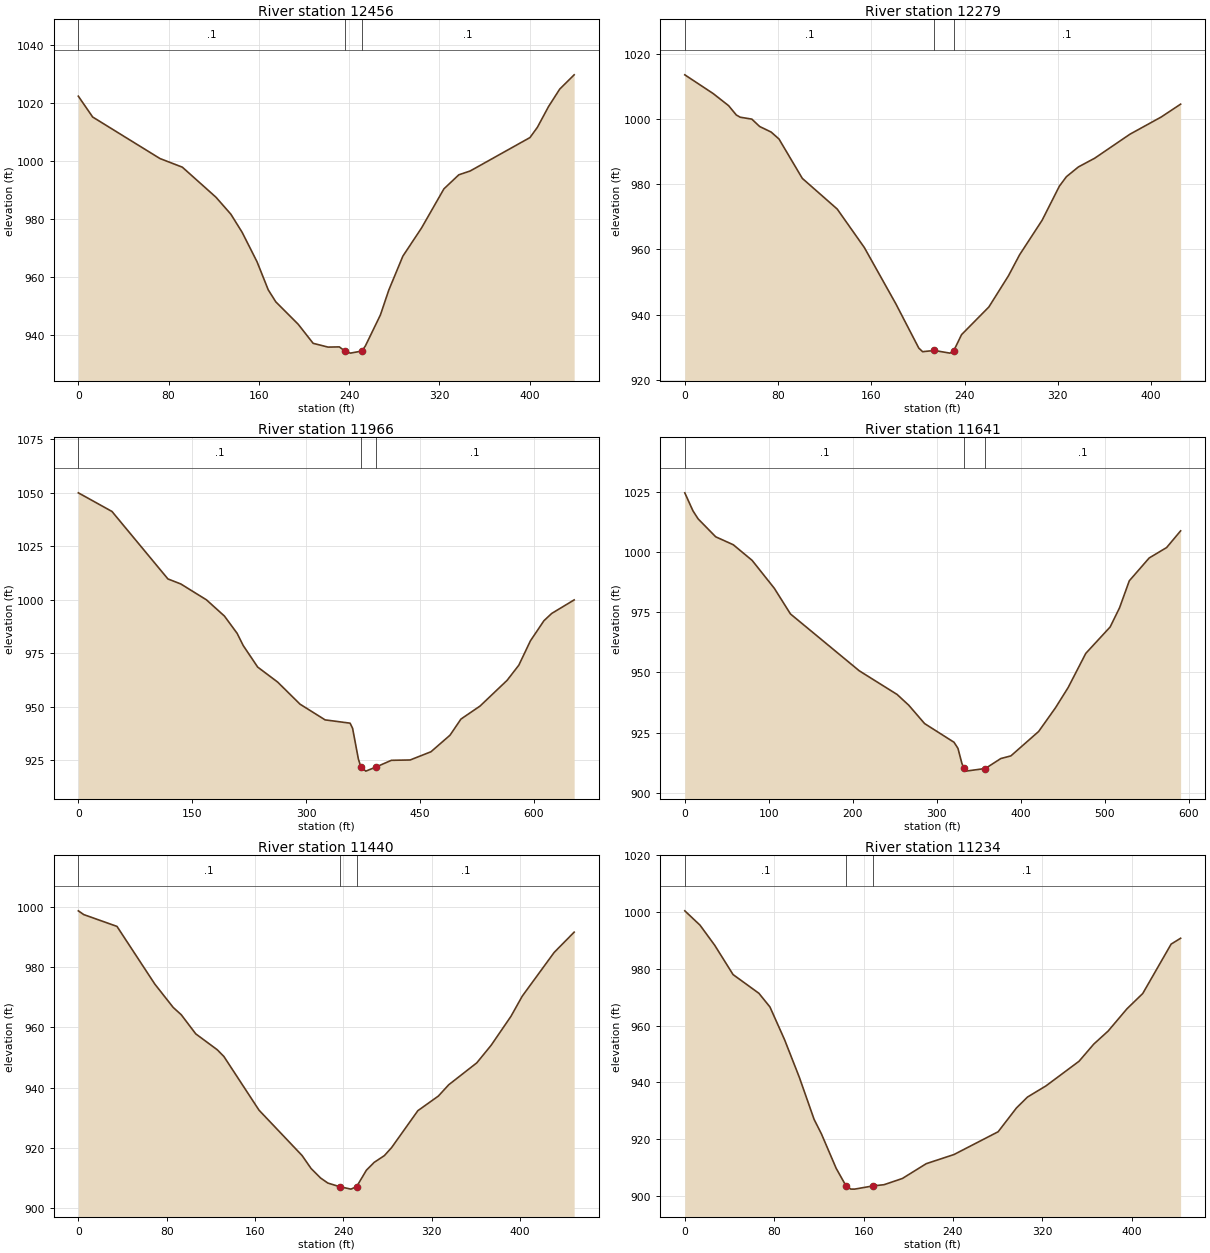
Type RM Length L Ch R = 1 ,12456   ,175.3,176.5,175.8
XS GIS Cut Line= 2
  1632567.786031477666.8688716341632132.49158943477606.976881288
#Sta/Elev= 30
       0 1022.45    12.7 1015.27    72.3 1000.95    92.2  997.96     122  987.59
   135.2  981.73   145.2  975.47   158.4  965.31   168.3  955.65     175  951.51
   194.8   943.8   208.1   937.2   221.3   935.9   231.3  935.97   236.1934.5792
   241.2  933.82   251.3934.5457   254.4  936.31   267.7  946.99   275.1  955.53
   287.6  967.27   304.1  976.96     324  990.49   337.2  995.34   347.2  996.64
   400.2 1008.17   406.8  1011.7   416.7 1018.87   426.6 1024.89   439.4 1029.82
#Mann= 3 ,-1,0
       0      .1       0   236.1    .045       0   251.3      .1       0
Bank Sta=236.1,251.3
XS Rating Curve= 0 ,0
Exp/Cntr(USF)=0,0
Exp/Cntr=0.3,0.1

Type RM Length L Ch R = 1 ,12279   ,322.5,313.7,302
XS GIS Cut Line= 6
1632588.98140918477505.0429910871632502.68597808477490.573859915
1632428.71827826477478.1716537621632330.42812051477459.650037259
1632257.13200726477443.2435740081632171.62135151477424.094334096
#Sta/Elev= 30
       0 1013.47    24.3 1007.74    37.6 1004.01    44.2 1001.16    47.5 1000.48
    57.5  999.89    64.2  997.63    74.1  995.92    80.8  993.79   100.8  981.73
   130.7  972.34     154  960.53   181.1  943.23   200.7  929.71     204   928.6
   214.1  928.97   227.4  928.16   230.7  928.89   237.4  933.83   260.8   942.3
   277.6  951.85   287.2  958.32   306.5  968.89   321.3  979.34   327.3  982.23
   337.6  985.23   351.6  987.91   381.8  995.26   408.7 1000.55   425.3 1004.48
#Mann= 3 ,-1,0
       0      .1       0   214.1    .045       0   230.7      .1       0
Bank Sta=214.1,230.7
XS Rating Curve= 0 ,0
Exp/Cntr(USF)=0,0
Exp/Cntr=0.3,0.1

Type RM Length L Ch R = 1 ,11966   ,319.6,324.5,319.7
XS GIS Cut Line= 6
1632797.57288314477213.5743868781632575.88264967477157.699886183
1632446.39513755 477147.568145171632410.27715002477188.642543051
1632376.86109851477213.5704769191632193.57078268477288.557203591
#Sta/Elev= 30
       0 1049.99    44.3 1041.29     118 1009.76   134.9 1007.43   168.7 1000.01
   192.4  992.43   209.1  984.37   217.2  978.63   236.2   968.6   262.5  961.59
     292  951.26     325  943.93   357.9  942.39   361.2  940.01   368.8  925.67
372.1305921.8781   378.6  919.99391.5905921.8359   412.3  925.04     437   925.2
   464.4  929.03   489.5  936.77   503.9   944.3   529.1   950.4   564.7  962.41
   580.1  969.46   595.4  980.85   613.2  990.25   623.4  993.64     653  999.97
#Mann= 3 ,-1,0
       0      .1       0372.1305    .045       0391.5905      .1       0
Bank Sta=372.1305,391.5905
XS Rating Curve= 0 ,0
Exp/Cntr(USF)=0,0
Exp/Cntr=0.3,0.1

Type RM Length L Ch R = 1 ,11641   ,201.9,201,196.4
XS GIS Cut Line= 3
1632569.36816535476732.7646306171632260.95282513 476981.11367336
1632101.90051462477092.798929103
#Sta/Elev= 30
       0 1024.55     9.7 1017.08    15.9 1013.72    36.8 1006.29    57.7    1003
    80.2  996.49   106.6   984.9   125.8  974.26   207.7  950.66   252.8  940.82
   266.7  936.34   285.5  928.74   320.5  920.99   325.2  918.47   329.8  912.34
   332.2  910.11   334.5     909  357.85  910.09   376.2  914.22   388.2  915.32
   421.3  925.47   441.3   935.3   456.4   943.7   477.4  957.89   506.4  968.86
   517.6  976.82   529.2  988.02   552.9  997.51   573.6 1001.82   590.3 1008.76
#Mann= 3 ,-1,0
       0      .1       0   332.2    .045       0  357.85      .1       0
Bank Sta=332.2,357.85
XS Rating Curve= 0 ,0
Exp/Cntr(USF)=0,0
Exp/Cntr=0.3,0.1

Type RM Length L Ch R = 1 ,11440   ,211.4,205.8,195.4
XS GIS Cut Line= 2
1632305.41636055476640.5323796631632016.45682264476984.001852424
#Sta/Elev= 30
       0  998.74     4.9  997.49      35  993.56    69.3  974.36    85.9  966.62
    93.2  964.19   106.3  957.84   125.8  952.55   131.8  950.31   163.6  932.47
   202.6  917.38   210.7  913.09   219.3  909.92   225.9  908.24   236.5  907.04
   246.8  906.22  251.94  907.04   260.8  912.51   267.8   915.1   277.1  917.37
   283.6  920.02   307.4   932.3     326  937.17   335.3   940.9   360.8  948.22
   373.7  954.02   391.7  963.68   401.9  970.37   430.8  984.91   448.9  991.65
#Mann= 3 ,-1,0
       0      .1       0   236.5    .045       0  251.94      .1       0
Bank Sta=236.5,251.94
XS Rating Curve= 0 ,0
Exp/Cntr(USF)=0,0
Exp/Cntr=0.3,0.1

Type RM Length L Ch R = 1 ,11234   ,267.9,274.4,273.9
XS GIS Cut Line= 2
1632024.79716166476525.7922215611631985.61987225476967.712046065
#Sta/Elev= 30
       0 1000.41    13.6  995.37    26.8  988.26    43.2  977.95    66.3  971.36
    76.2  966.54    89.3  954.99   102.5  941.75   115.7  926.95   122.3  921.79
   135.5  909.66  144.29  903.49   148.6  902.37   151.9  902.36   168.4  903.49
   178.3  903.92   194.7  906.11   216.1  911.33   240.9  914.55   280.4  922.57
   296.8  930.96   306.7  934.81   323.2  938.73   352.8  947.41     366  953.46
   378.8  958.04   395.7   965.9   409.8  971.28   435.2  988.68   443.7  990.75
#Mann= 3 ,-1,0
       0      .1       0  144.29    .045       0   168.4      .1       0
Bank Sta=144.29,168.4
XS Rating Curve= 0 ,0
Exp/Cntr(USF)=0,0
Exp/Cntr=0.3,0.1

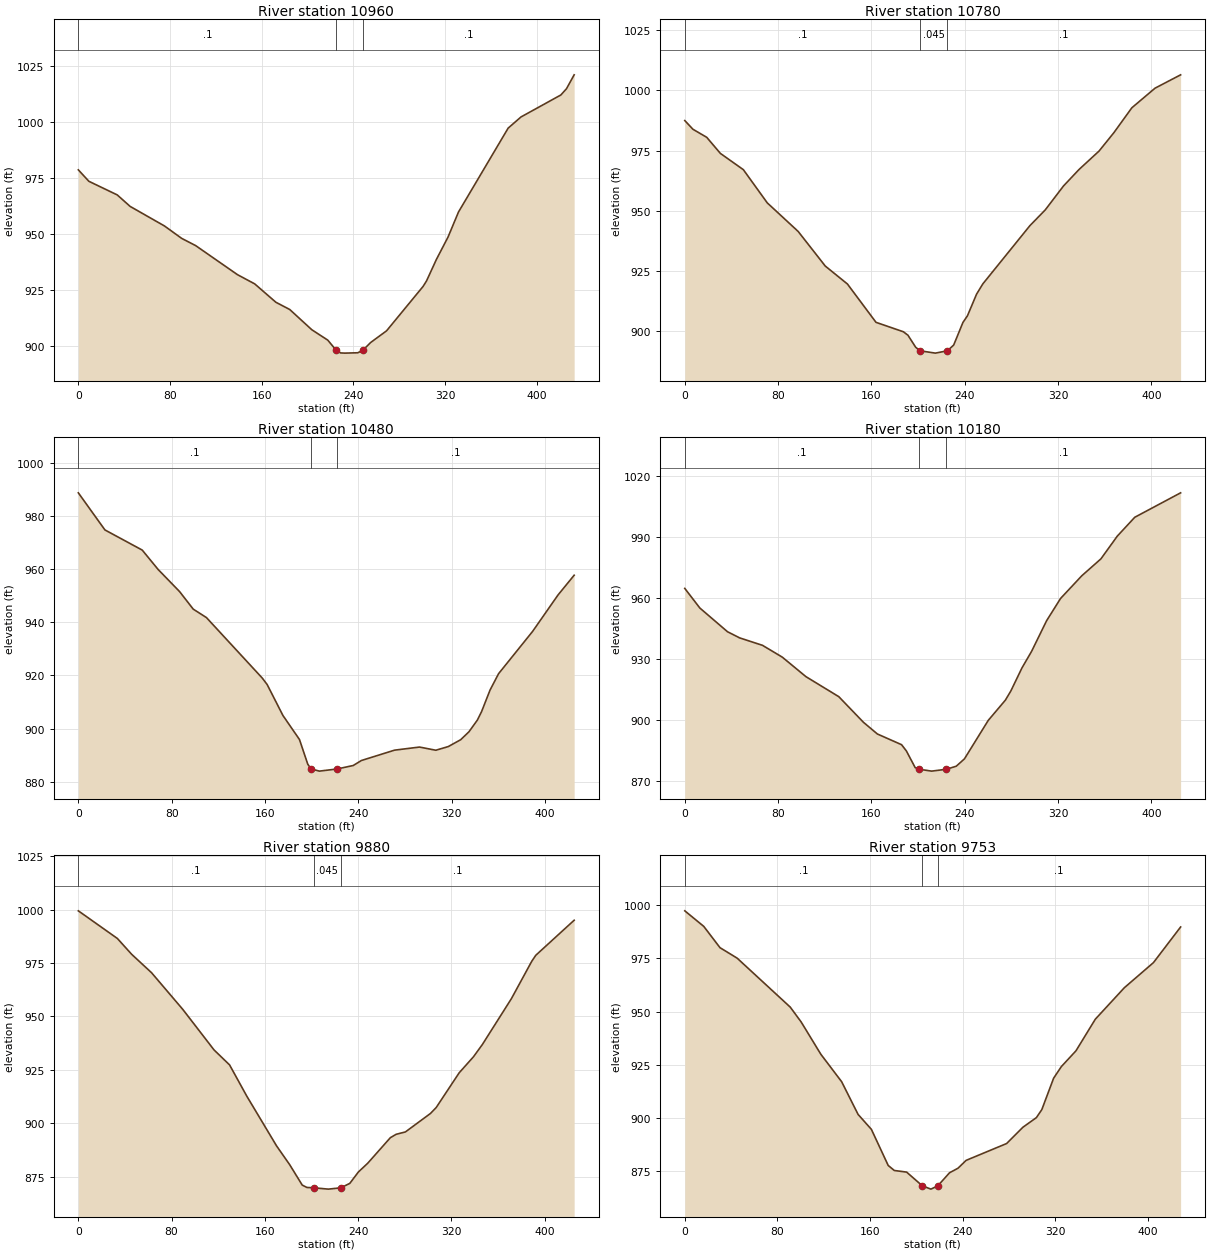
Type RM Length L Ch R = 1 ,10960   ,179,179.4,180.7
XS GIS Cut Line= 2
1631913.35776149476516.1340513871631704.10744893476894.898942665
#Sta/Elev= 30
       0  978.59     9.2  973.48      34  967.38    45.2  962.26    75.2  953.51
    90.2  947.97   102.4  944.74   138.9  931.75   153.9  927.65   172.4  919.43
   184.5  916.19   203.8  907.13   217.7   902.5   225.1  897.94   228.9  896.79
   232.6   896.7   243.9  896.86  248.22  897.94   255.1  901.44     269  906.67
   300.9  926.53   303.9  928.99   312.5  938.58   322.6  948.52   331.8  959.79
   375.1  997.23   386.3 1002.22   421.1 1012.05     426 1014.83   432.7 1021.05
#Mann= 3 ,-1,0
       0      .1       0   225.1    .045       0  248.22      .1       0
Bank Sta=225.1,248.22
XS Rating Curve= 0 ,0
Exp/Cntr(USF)=0,0
Exp/Cntr=0.3,0.1

Type RM Length L Ch R = 1 ,10780   ,302.5,300,298.3
XS GIS Cut Line= 6
1631771.22385834 476438.31349726 1631723.2994135476511.522012249
1631682.22141168476574.2722148451631627.45052384476657.939042255
1631586.37252201476720.6892448371631538.44807717476793.898087919
#Sta/Elev= 30
       0   987.5       7  983.89    18.8  980.55    30.5  973.87    50.2   967.1
    70.7  953.31    97.2  941.43   120.4  927.07   139.4  919.61   163.9  903.68
   187.4  899.76   191.3  898.31   197.9  893.33   201.6891.8571   214.8  890.89
   225.1891.8629   230.5  894.26   238.4  903.62   242.3  906.42   250.1   915.4
   255.5  919.68   295.8  943.84     309  950.41   324.6  960.33   337.8  967.12
   355.1  974.85   367.8  982.48   383.2  992.82   403.1 1000.97     425 1006.51
#Mann= 3 ,-1,0
       0      .1       0   201.6    .045       0   225.1      .1       0
Bank Sta=201.6,225.1
XS Rating Curve= 0 ,0
Exp/Cntr(USF)=0,0
Exp/Cntr=0.3,0.1

Type RM Length L Ch R = 1 ,10480   ,296.6,300,302.7
XS GIS Cut Line= 6
1631498.27230451476239.3765591681631464.56633517476320.127053842
1631436.24027634476389.5724530071631398.47165109476482.165443674
1631370.14526418476551.6108428391631331.97440876476630.487325504
#Sta/Elev= 30
       0   988.8    22.8  974.82    54.8  967.22    68.4  959.93    86.8   951.6
    98.5  944.98   109.8  941.81   157.7     919   161.9  916.56   175.4  904.92
   189.6  895.85   196.7  886.57   199.5 884.758   206.7  883.94   221.9884.7556
   235.7  886.06   242.7  887.94   271.1  891.84   292.5  893.01   306.5  891.81
   317.2   893.2   327.8  895.77   334.9  898.76   342.1  903.16   345.7  906.34
     353  914.49   360.3  920.65   389.5   936.6   411.3  950.33   425.1  957.75
#Mann= 3 ,-1,0
       0      .1       0   199.5    .045       0   221.9      .1       0
Bank Sta=199.5,221.9
XS Rating Curve= 0 ,0
Exp/Cntr(USF)=0,0
Exp/Cntr=0.3,0.1

Type RM Length L Ch R = 1 ,10180   ,294.5,300,304.8
XS GIS Cut Line= 6
1631292.20808409476114.4447224291631237.09467725476182.449835762
1631191.51668443476242.0120525961631130.74646476476321.428560421
1631085.16847192476380.9907772541631031.99436568476450.479811504
#Sta/Elev= 30
       0  964.58    12.9  954.95    36.6  943.32      47   940.3    66.6  936.64
    83.5  930.87   103.9  921.24     132  911.44   153.1  898.88   165.1  893.11
   185.8  887.87   189.9  884.82   197.5  876.59     201 875.805   211.6  874.89
   224.3875.8146   232.7  877.31   239.7  880.91   260.1  899.79   274.8  909.74
   279.5  914.26     289  925.55   297.3  933.73   310.1   948.7   322.1  959.65
   340.3  970.79   356.7  979.09   370.7  990.23   385.7   999.5     425  1011.5
#Mann= 3 ,-1,0
       0      .1       0     201    .045       0   224.3      .1       0
Bank Sta=201,224.3
XS Rating Curve= 0 ,0
Exp/Cntr(USF)=0,0
Exp/Cntr=0.3,0.1

Type RM Length L Ch R = 1 ,9880    ,128.4,127.6,121.3
XS GIS Cut Line= 6
1631217.25547808475927.2351230831631139.35898034475967.089374095
1631072.59041309   476001.2503951630983.56565675476046.798204169
 1630915.9962381476079.3936114161630835.38222609476113.937177509
#Sta/Elev= 30
       0  999.42    33.5  986.48    45.7   979.1    62.8  970.46    89.6  953.29
   116.4  934.33   129.7  927.34   144.4  912.78     170  889.45   181.3  880.62
     192  871.12     196     870   201.7  869.86   214.4  869.22   225.1869.8283
   232.8  871.91   240.2  877.26   248.1  881.29   267.6  893.29   272.5  894.86
   280.5  895.98     302  904.63   306.9   907.4   326.6  923.64   338.9  931.17
   346.4   936.8   371.4  958.34   388.8  975.78   392.3  978.62   425.2  995.02
#Mann= 3 ,-1,0
       0      .1       0   201.7    .045       0   225.1      .1       0
Bank Sta=201.7,225.1
XS Rating Curve= 0 ,0
Exp/Cntr(USF)=0,0
Exp/Cntr=0.3,0.1

Type RM Length L Ch R = 1 ,9753    ,173.3,172.6,172.2
XS GIS Cut Line= 2
  1631089.392891475755.8483153941630823.85792947476091.902397857
#Sta/Elev= 30
       0  997.28    16.4  989.97    30.4  979.99    45.2  975.09    91.1   952.1
   100.5  945.15   117.5  930.01   135.5   917.1   149.7  901.76   161.2  894.75
   175.7  877.82     181  875.46   191.6  874.71  205.17  868.28   212.6  866.72
  218.55  868.26   228.7   874.4     236  876.53     243  880.21     278  888.11
     292  895.72   303.7  900.26   308.4  904.02   318.6  918.76   325.3  924.22
   337.9  931.61   354.6  946.43   379.7  961.21   404.8  972.97   428.3   989.7
#Mann= 3 ,-1,0
       0      .1       0  205.17    .045       0  218.55      .1       0
Bank Sta=205.17,218.55
XS Rating Curve= 0 ,0
Exp/Cntr(USF)=0,0
Exp/Cntr=0.3,0.1

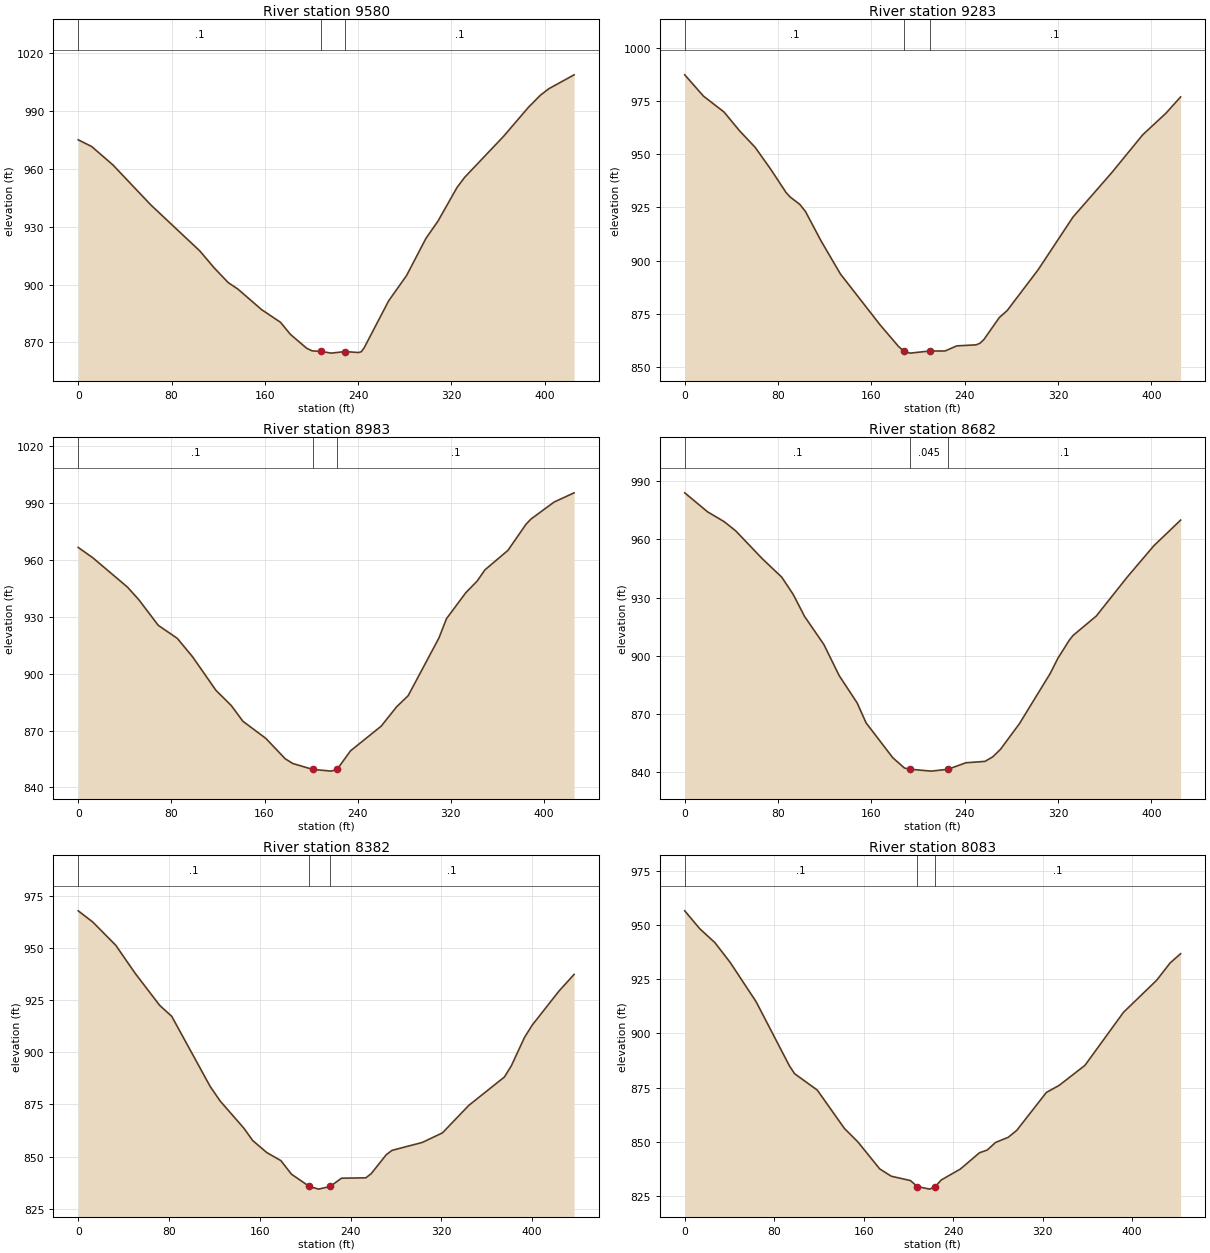
Type RM Length L Ch R = 1 ,9580    ,287.4,297.4,303.7
XS GIS Cut Line= 6
1630958.33047101475642.0480294231630901.73511176475709.041661844
1630857.30606675475769.4654255061630798.06701201475850.030881166
1630753.63763893 475910.454316751630701.80309692 475980.94859834
#Sta/Elev= 30
       0  975.11    11.5  971.64    29.7  962.11    62.3  941.29   104.3  917.43
   116.5  908.71   128.7  900.97   136.9  897.66   157.2  887.01   173.5  880.39
   181.9  874.18   195.8  866.98   200.5   865.6   208.5865.2605     217  864.41
   228.7  865.22   240.4  864.72   242.8  865.17   245.1  867.08   266.2  891.54
   281.6  904.72   298.2     924   308.5  932.92   324.9  950.45   331.4  955.65
   364.8  976.95   385.9  991.87   396.3  998.22   403.4 1001.56   425.2 1008.82
#Mann= 3 ,-1,0
       0      .1       0   208.5    .045       0   228.7      .1       0
Bank Sta=208.5,228.7
XS Rating Curve= 0 ,0
Exp/Cntr(USF)=0,0
Exp/Cntr=0.3,0.1

Type RM Length L Ch R = 1 ,9283    ,296.5,300.1,302.2
XS GIS Cut Line= 6
1630888.98120026475523.8976751711630802.71332817475538.563328251
1630728.63867317475550.3067430851630629.87213843 475565.96484825
1630555.79715534475577.7082630841630469.37639642475591.408695012
#Sta/Elev= 30
       0  987.35      16  977.37    33.7  969.86      47  961.03    60.3   953.3
    73.6  943.05    86.9  931.99    90.3  929.95    98.6  926.47   103.5  923.09
   116.8  909.32   133.4  893.77   167.4  869.85   183.3  859.63   187.8857.4963
   193.2  856.54   209.8  857.53   223.1  857.55   233.1  859.94   249.7  860.43
     253  861.18   256.3  862.85   269.6  873.25   276.4  876.58   302.9  895.74
   332.7  920.45     366  941.38   392.5  959.15   412.5  969.35     425  976.97
#Mann= 3 ,-1,0
       0      .1       0   187.8    .045       0   209.8      .1       0
Bank Sta=187.8,209.8
XS Rating Curve= 0 ,0
Exp/Cntr(USF)=0,0
Exp/Cntr=0.3,0.1

Type RM Length L Ch R = 1 ,8983    ,304.2,300.4,297.6
XS GIS Cut Line= 6
1630858.37922734475287.5743289291630771.12185593475277.208864093
1630696.32837035475268.3716114161630596.71898951475257.690530419
1630522.11415184 475250.342776091630435.07889284475241.770614758
#Sta/Elev= 30
       0   966.6    12.5  961.16    42.3  945.67    52.2   938.9    68.7  925.53
    85.2  918.57    98.4  908.73   118.3  891.19   131.5  883.15   141.4  874.91
   161.2  865.82   177.7  855.13   184.3   852.6   201.3849.5142   217.3  848.59
   222.3849.4966   233.8  859.28   260.2  872.34   273.4  882.52   283.3  888.38
   309.7  918.77   316.2  928.98   332.7  942.63   342.6  948.88   349.2  954.74
     369  965.05   384.6  978.89   388.8  981.58   408.6  990.52   425.8   995.4
#Mann= 3 ,-1,0
       0      .1       0   201.3    .045       0   222.3      .1       0
Bank Sta=201.3,222.3
XS Rating Curve= 0 ,0
Exp/Cntr(USF)=0,0
Exp/Cntr=0.3,0.1

Type RM Length L Ch R = 1 ,8682    ,308.4,300,291.1
XS GIS Cut Line= 6
1630905.82762326474955.7282078421630818.52136743474961.548734263
 1630743.6875276474966.5382255911630643.90918384474973.190443262
1630569.07534401474978.1796065121630481.76908818474984.000132918
#Sta/Elev= 30
       0  984.03    19.6  974.23    33.7  969.22    43.6  964.49    66.6  950.01
    83.1  940.62    92.9  931.77   102.8  920.27   119.2  905.95   132.4  889.84
   147.8  875.78   155.4  865.54   178.4   847.5   188.3  842.26   193.1841.6382
   211.3  840.66   225.7841.6285   240.9  844.96   257.3  845.68   263.9  847.97
   270.5  851.81   286.9  865.15   313.2  890.94   319.8  898.77   329.7  908.22
   332.9   910.6   352.7  920.55   379.1  940.53     402  956.74     425  969.98
#Mann= 3 ,-1,0
       0      .1       0   193.1    .045       0   225.7      .1       0
Bank Sta=193.1,225.7
XS Rating Curve= 0 ,0
Exp/Cntr(USF)=0,0
Exp/Cntr=0.3,0.1

Type RM Length L Ch R = 1 ,8382    ,292.6,299.3,302.1
XS GIS Cut Line= 6
1630755.42963009474518.4518514281630701.70959318474587.520282835
1630655.66408159474646.721608013 1630594.2705036474725.657145679
 1630536.1994255474776.6370305871630459.48566817474836.162502095
#Sta/Elev= 30
       0  967.93    12.9  962.53    33.1   951.4    50.3  937.86    71.7  922.63
    82.4   917.3   116.3  883.63   125.1  876.65   145.9  863.67   153.7  857.73
   166.1  851.95   178.6  848.06   187.9  841.55   203.6835.6862   211.8  834.39
     222835.6824     232  839.64   253.4  839.81   258.1  841.78   271.5  850.96
   276.5  852.99   303.1  856.78   320.9  861.38   344.1  874.56   375.5  888.19
   381.6  893.56   393.2  907.17   400.1  913.17   423.6  929.43   436.9  937.42
#Mann= 3 ,-1,0
       0      .1       0   203.6    .045       0     222      .1       0
Bank Sta=203.6,222
XS Rating Curve= 0 ,0
Exp/Cntr(USF)=0,0
Exp/Cntr=0.3,0.1

Type RM Length L Ch R = 1 ,8083    ,303.1,300.1,296.9
XS GIS Cut Line= 6
  1630567.055663 474411.772930921630499.80973451474474.931925341
1630436.05854967474520.5394456681630339.53905767474550.196210504
1630270.72095384474589.8956061751630195.15548818474642.833492428
#Sta/Elev= 30
       0  956.46    13.5  948.17      27  941.78    40.7  932.62    63.8  914.57
    93.6  884.98    98.3  881.34   118.5  873.82   142.7  856.17   154.8  849.93
   174.3  837.49   184.6  834.12   201.8   832.1   207.9829.3483     219  828.16
   224.1  829.35   229.2  832.35   246.4  837.42   263.6  844.96   270.4  846.17
   277.9  849.69   289.2  852.05   296.8  855.24   323.3  872.74   334.7  875.98
   357.8  885.23   392.2  909.66   421.9  924.46   433.9  932.42   443.3   936.7
#Mann= 3 ,-1,0
       0      .1       0   207.9    .045       0   224.1      .1       0
Bank Sta=207.9,224.1
XS Rating Curve= 0 ,0
Exp/Cntr(USF)=0,0
Exp/Cntr=0.3,0.1

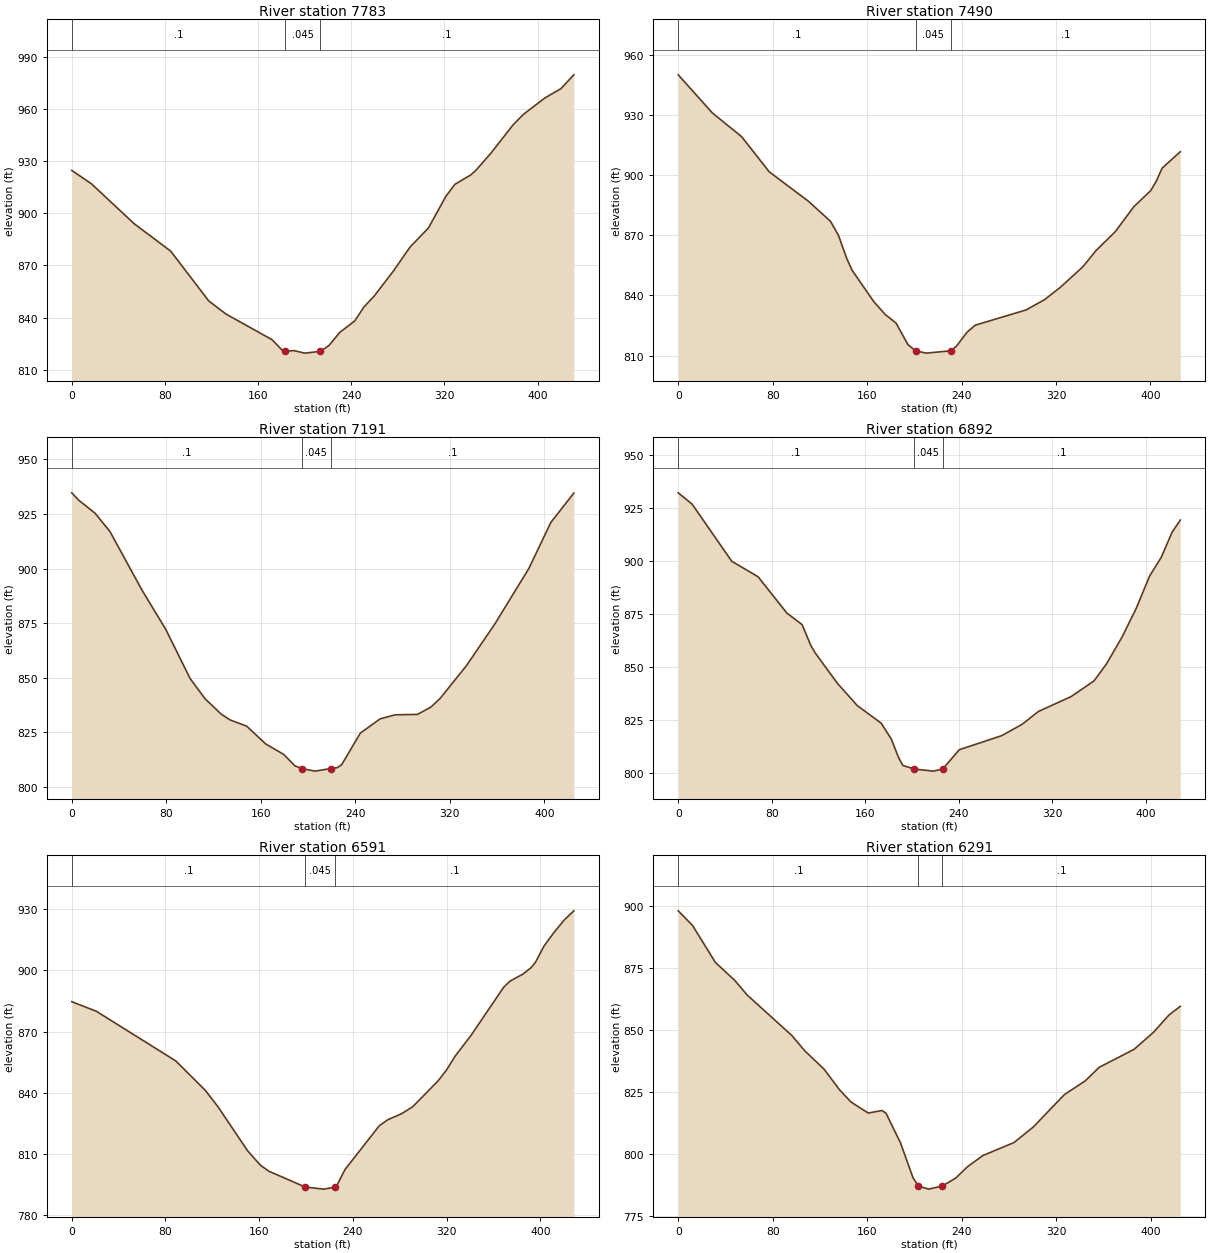
Type RM Length L Ch R = 1 ,7783    ,291.1,292.5,290.5
XS GIS Cut Line= 6
1630349.47834225474205.4757713381630272.53427042474255.801130012
1630211.47238468474302.3095671681630138.12148151474370.299916759
1630084.01791517 474422.24042967 1630020.8973065474482.837421343
#Sta/Elev= 30
       0  924.68    16.7   917.1    53.6  894.01      85  878.21   117.6   849.6
   132.3  842.08   172.1  827.22   180.4   821.4   183.5 820.555   190.7  820.99
     200  819.52   213.6820.5368   220.9  823.92   230.1   831.4     243  838.07
     251  846.12   259.7  852.34   276.6  867.12   290.5  880.54   306.3  891.55
   321.4  909.89     329  916.65   342.7  922.12   347.2  924.82   360.1  934.72
     379   950.9   387.7  956.84   406.3  966.39     420  971.69   431.2  979.71
#Mann= 3 ,-1,0
       0      .1       0   183.5    .045       0   213.6      .1       0
Bank Sta=183.5,213.6
XS Rating Curve= 0 ,0
Exp/Cntr(USF)=0,0
Exp/Cntr=0.3,0.1

Type RM Length L Ch R = 1 ,7490    ,303.1,299.5,294.8
XS GIS Cut Line= 6
1630196.35856976473926.1689152571630133.91414084473987.728503421
1630080.30893309474040.399985999  1630007.895364474109.466777012
1629953.17860992474160.7143779251629889.34606043474220.499363333
#Sta/Elev= 30
       0  949.92      29  930.87    53.7   919.1    77.1  901.57   110.2  886.96
     129  876.89   135.7  869.95   142.8  858.31   147.3  852.48   165.7  836.84
   175.2  830.54   184.5   826.2   194.6  815.42     201812.3565     210  811.21
   231.1812.3847   235.5  814.58   244.8  821.72   251.6  825.14   294.7  832.74
   310.4  837.91   323.9  844.12   342.7  854.21   353.9  862.33   370.1  871.67
   385.9  884.16   400.3  892.25     405  896.98   409.9  903.39   425.3  911.61
#Mann= 3 ,-1,0
       0      .1       0     201    .045       0   231.1      .1       0
Bank Sta=201,231.1
XS Rating Curve= 0 ,0
Exp/Cntr(USF)=0,0
Exp/Cntr=0.3,0.1

Type RM Length L Ch R = 1 ,7191    ,299.7,298.9,299
XS GIS Cut Line= 6
1629900.93986925473725.8625573371629857.71324967   473801.939833
1629820.66279884473867.1490201651629771.26132284473954.094384342
1629734.21054393474019.303571507 1629690.9845805 474095.38117525
#Sta/Elev= 30
       0  934.72     5.9  931.34    19.7  925.39    32.3     917    59.5  890.07
    79.5  872.19   100.2  849.59   112.7  840.41   126.6  833.22   134.2  830.57
     148   827.8   164.3  819.55   179.4  814.82   188.9  809.57   194.6  808.35
   205.9  807.15   219.6808.3477     225  808.78   228.5  810.14   244.3   824.6
   261.1  831.13   273.8  832.97   292.6  833.15     304  836.51   311.7   840.4
   334.2  855.57   358.4  874.83     387  900.12   405.5  921.12     425  934.62
#Mann= 3 ,-1,0
       0      .1       0   194.6    .045       0   219.6      .1       0
Bank Sta=194.6,219.6
XS Rating Curve= 0 ,0
Exp/Cntr(USF)=0,0
Exp/Cntr=0.3,0.1

Type RM Length L Ch R = 1 ,6892    ,297.7,301.1,297
XS GIS Cut Line= 6
1629633.40562743473589.345441923 1629590.5713955473665.643845752
1629553.85657392473731.0426650941629506.78645809473819.298722178
1629480.64346576   473890.6325691629462.50373825473979.909293339
#Sta/Elev= 30
       0  932.04    11.9   926.7    45.8  899.78    68.3   892.5      93  875.34
     106  869.94   113.5  860.05   117.1  856.67   136.1  842.34   153.2  831.77
   173.6  823.52   182.3  816.01   188.4  807.45   192.2  803.56   201.8801.8958
   218.2  800.89   226.3 801.884   240.5  810.98   276.8  817.61   294.2  822.92
   308.2     829   336.2  836.02   355.7  843.39   366.4  851.39   379.8  864.12
   391.9  877.61   403.2   892.7   413.3  901.66   422.5  913.39   429.6  919.21
#Mann= 3 ,-1,0
       0      .1       0   201.8    .045       0   226.3      .1       0
Bank Sta=201.8,226.3
XS Rating Curve= 0 ,0
Exp/Cntr(USF)=0,0
Exp/Cntr=0.3,0.1

Type RM Length L Ch R = 1 ,6591    ,302.9,300,293.9
XS GIS Cut Line= 6
1629320.63656792473555.2073868361629290.72947551473641.259052008
1629259.30007643473709.3560286761629217.39333609473800.151450753
1629185.96360892473868.2480993421629149.29537517473947.694462761
#Sta/Elev= 30
       0  884.58    20.9  879.93    88.8   855.6     114  841.21   124.9  833.11
   150.1  811.64     161   804.6   168.2  801.64   199.4793.8752   215.2  792.87
     225793.8815     226   794.3   233.3  802.51   262.5  823.87   269.9  826.86
   281.5  829.75   291.1  833.21   312.8  845.91     320  851.24   327.2  857.89
   341.1  868.31   368.7  891.66   374.2  894.69     385  898.04   392.2  901.29
   395.9  903.91   403.1  911.78   410.8  917.83   420.7  924.77   428.6  929.05
#Mann= 3 ,-1,0
       0      .1       0   199.4    .045       0     225      .1       0
Bank Sta=199.4,225
XS Rating Curve= 0 ,0
Exp/Cntr(USF)=0,0
Exp/Cntr=0.3,0.1

Type RM Length L Ch R = 1 ,6291    ,304.2,300,293.1
XS GIS Cut Line= 6
1628968.87250768473440.2742177551628970.15892242473527.764856428
1628971.26161051473602.7568324211628972.73175192 473702.74613376
1628973.83476809473777.7377816741628975.12151092473865.228420332
#Sta/Elev= 30
       0  898.25    12.1  892.35    31.5  877.38    47.9  870.13    58.2  864.33
    96.2  847.89     107  841.77   123.4  834.34   136.5  826.01   146.3  821.02
   160.8   816.6   172.6  817.62   175.9   816.5   188.1   804.6   198.8  790.41
   203.3787.1144     212  785.87   223.6787.1308   234.9  790.34   244.8  794.89
   257.8  799.41   284.2  804.68   300.6  810.98   326.8  824.01   344.6  829.62
   356.3  835.05   385.9  842.33   402.3  849.19   415.4  856.18     425  859.69
#Mann= 3 ,-1,0
       0      .1       0   203.3    .045       0   223.6      .1       0
Bank Sta=203.3,223.6
XS Rating Curve= 0 ,0
Exp/Cntr(USF)=0,0
Exp/Cntr=0.3,0.1