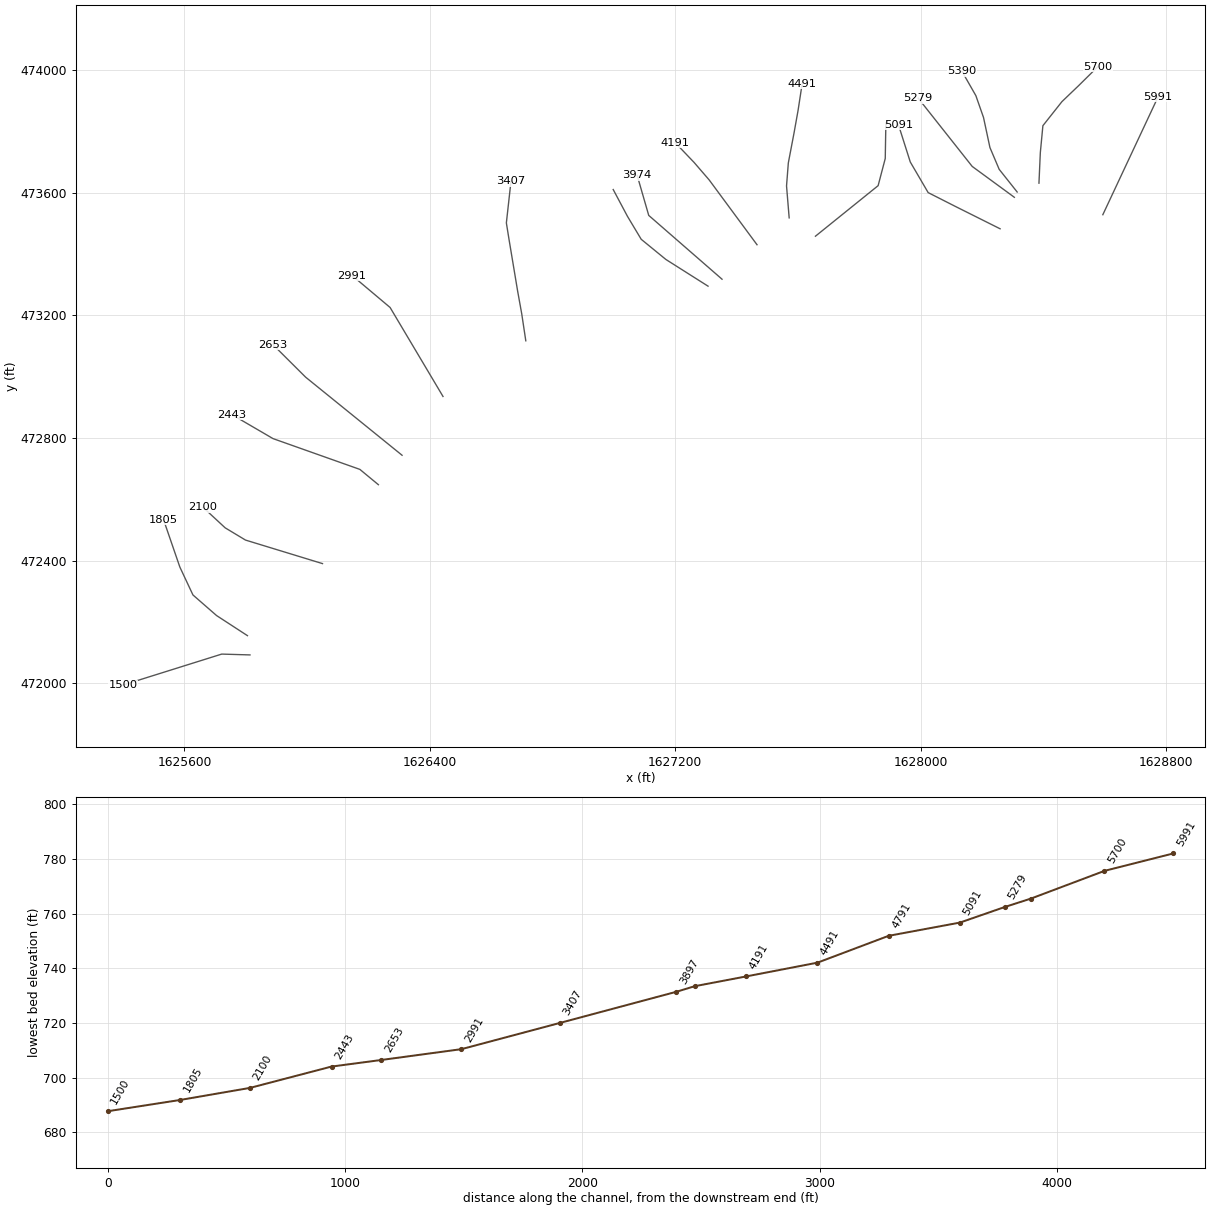
HEC-RAS study LwrBwmRn.prj: LwrBwmRn

--- LwrBwmRn.g01 (geometry) --- (continued)

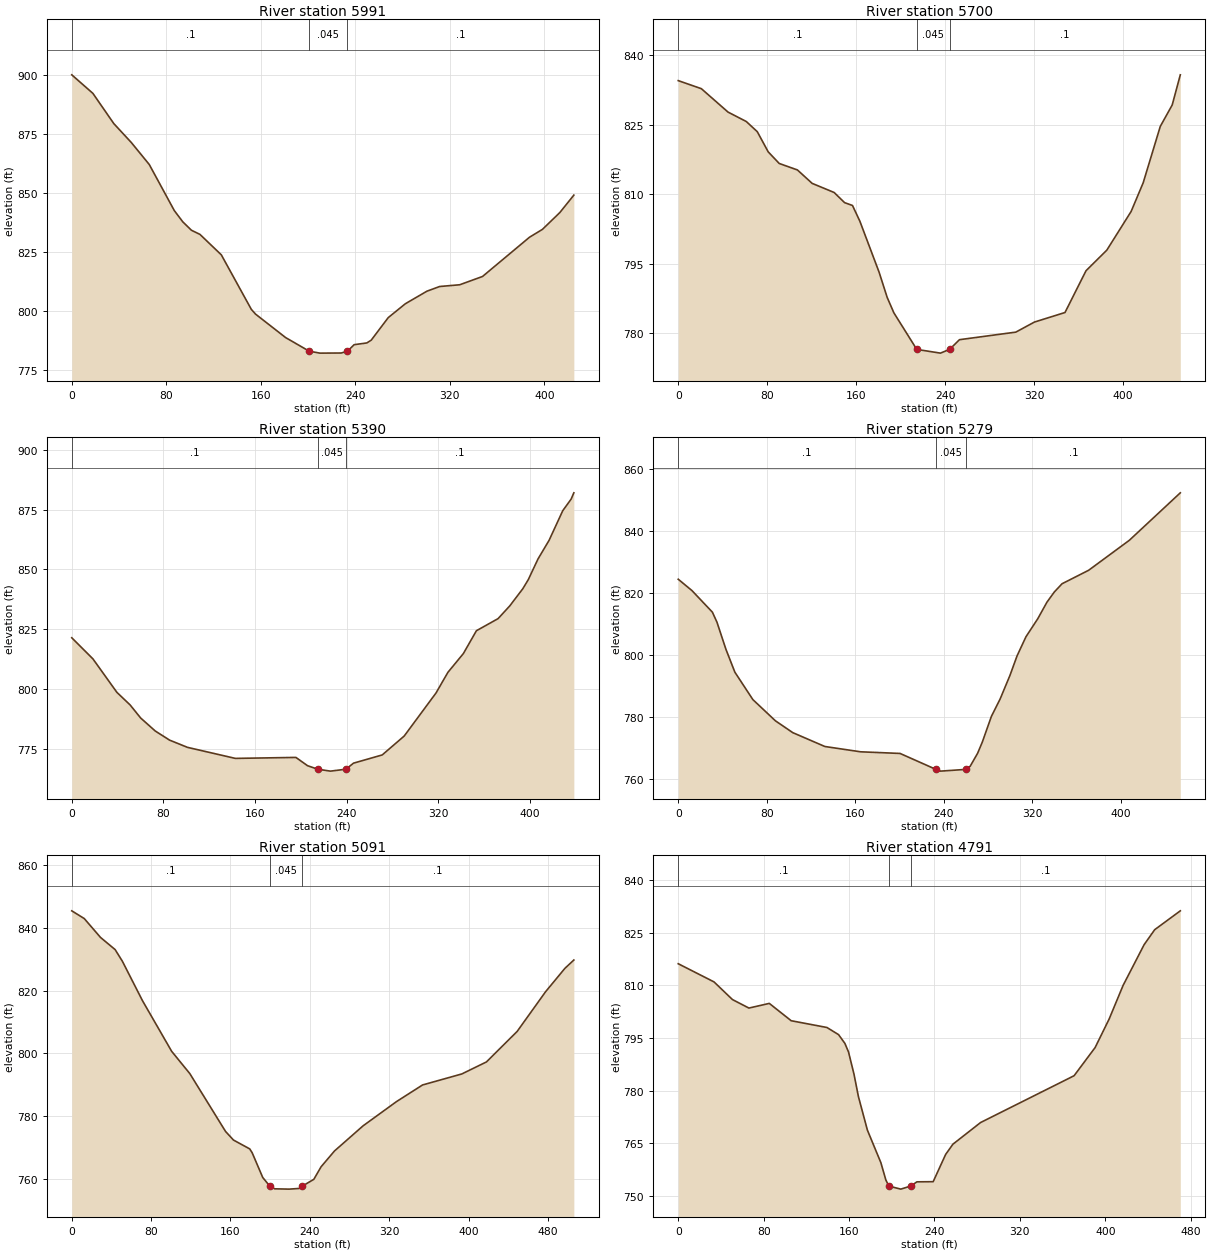
Type RM Length L Ch R = 1 ,5991    ,295.4,290.5,288.7
XS GIS Cut Line= 6
1628593.70888792473527.7143315821628630.84660892473606.941863418
1628662.67922242473674.8515045051628705.12270708473765.397255167
 1628736.9553206473833.3065681761628774.09304158 473912.53442809
#Sta/Elev= 30
       0  900.22    17.9  892.34    35.6  879.51    50.4  871.49    65.6  862.15
    86.8  842.59      94   837.8   101.3  834.24   108.5  832.49   126.6   823.8
     152  800.65   155.6  798.63     181  788.69     201   782.9     210  782.08
   228.1  782.13   233.4782.8857     239  785.66   249.8  786.41   253.5  787.59
   267.9  797.16   282.4  803.05   300.6  808.36   311.4  810.36   328.4   811.1
   347.7  814.62   387.5  831.29   398.4  834.61   413.1  841.73     425  849.15
#Mann= 3 ,-1,0
       0      .1       0     201    .045       0   233.4      .1       0
Bank Sta=201,233.4
XS Rating Curve= 0 ,0
Exp/Cntr(USF)=0,0
Exp/Cntr=0.3,0.1

Type RM Length L Ch R = 1 ,5700    ,279.4,310,308.4
XS GIS Cut Line= 6
1628385.47013117473630.4165540041628389.92812751473730.043979421
1628398.28703468473817.8508904281628460.36433834473896.272977665
1628514.82715592473948.4618496751628577.56554751474010.365925342
#Sta/Elev= 30
       0  834.47    20.8  832.73    44.8  827.68    61.2  825.65    71.1  823.45
    80.9  819.11    90.8   816.6   107.2   815.2   120.4  812.31   140.2  810.34
   149.6  808.15   156.7  807.54   163.3  804.17   180.6  793.17   187.9  787.71
   193.9  784.39   214.5 776.493   235.8  775.69   244.1 776.508   252.9  778.59
   303.6  780.22   320.3  782.39   347.8  784.45   366.7  793.46   385.4   797.9
   407.3  806.26   418.1  812.42   433.5   824.6   444.2  829.21   451.5  835.72
#Mann= 3 ,-1,0
       0      .1       0   214.5    .045       0   244.1      .1       0
Bank Sta=214.5,244.1
XS Rating Curve= 0 ,0
Exp/Cntr(USF)=0,0
Exp/Cntr=0.3,0.1

Type RM Length L Ch R = 1 ,5390    ,105.7,111,117.3
XS GIS Cut Line= 6
1628314.46699233473601.6413490921628255.77813335473675.635951757
1628225.64302301473746.6718989161628204.78512509473844.477805674
1628179.81339025473915.7417707591628134.48113184473995.145811424
#Sta/Elev= 30
       0  821.39    18.5  812.54    39.4  798.55      51  793.25    60.2  787.79
    72.9  782.36    85.5  778.52   101.1   775.5   142.9  770.88   195.8  771.29
   205.9  767.84   214.9766.3439     226  765.55   239.5766.3489   246.1  768.88
   271.2  772.33   290.4  780.24   318.2  798.27   328.6  806.92   342.1  814.78
   353.5  824.34   372.4   829.4   382.6  834.72     394  841.91   398.8  845.72
   407.3  854.39     417  862.21   428.9  874.59   436.2  879.43   438.6  882.08
#Mann= 3 ,-1,0
       0      .1       0   214.9    .045       0   239.5      .1       0
Bank Sta=214.9,239.5
XS Rating Curve= 0 ,0
Exp/Cntr(USF)=0,0
Exp/Cntr=0.3,0.1

Type RM Length L Ch R = 1 ,5279    ,177,188.2,187.6
XS GIS Cut Line= 3
1628305.26876144473584.426897118 1628167.9064134473685.030306952
1627991.85044619473907.518617161
#Sta/Elev= 30
       0  824.41    12.4  820.75    30.9  813.77      35  810.56    43.1  801.82
    51.2  794.41    67.5  785.54    87.8  778.72   103.6  774.87   132.6   770.4
   164.9  768.69   200.6  768.16     233  763.02   237.2  762.45  260.57  763.02
     264  764.03   270.7  768.21   274.9  771.77   283.2  780.15   291.1  785.76
     300   793.4   306.3  799.59   314.4  805.82   325.1  811.65   333.4     817
   340.1   820.3   347.1  822.96   371.1   827.3   407.9  836.98     454  852.31
#Mann= 3 ,-1,0
       0      .1       0     233    .045       0  260.57      .1       0
Bank Sta=233,260.57
XS Rating Curve= 0 ,0
Exp/Cntr(USF)=0,0
Exp/Cntr=0.3,0.1

Type RM Length L Ch R = 1 ,5091    ,326.4,300.3,271.5
XS GIS Cut Line= 6
1628258.82930835473481.7849615071628180.56699768473520.916116834
1628113.48511083473554.4573883411628024.31238893473599.718452677
1627965.98015651473699.5315732511627927.23384292473821.516565502
#Sta/Elev= 30
       0  845.47    12.6     843      29  836.98    43.7  833.12      51  829.41
    71.3  816.82   100.7  800.69     119  793.59     155  775.16     163  772.41
   179.4  769.59   181.9  768.33   192.5  760.48   199.7   757.7   204.5  756.87
     219  756.77   229.2  756.98   232.3  757.71     244  759.89   251.3  763.89
   264.8  768.92   293.6  776.93   327.3  784.66   353.6  789.97   393.2  793.48
     418  797.31     449  807.05   477.6  819.68   497.1  827.14   506.1  829.79
#Mann= 3 ,-1,0
       0      .1       0   199.7    .045       0   232.3      .1       0
Bank Sta=199.7,232.3
XS Rating Curve= 0 ,0
Exp/Cntr(USF)=0,0
Exp/Cntr=0.3,0.1

Type RM Length L Ch R = 1 ,4791    ,292.1,300,307.7
XS GIS Cut Line= 6
1627656.84297951473457.5993143321627724.95439184473512.527354091
1627783.33583675473559.6082966771627861.17688842473622.384089753
1627884.41273434473710.8642277571627886.45013183473827.182892755
#Sta/Elev= 30
       0  816.19    33.5  811.01    50.8  805.97    66.2  803.55    85.3  804.88
   105.8  799.94   139.3  798.01   150.2  795.97   156.1  793.48   159.5  791.04
   164.6  784.75   168.8  778.29   177.2  768.75   189.8  759.48   194.5  754.53
   197.3752.7867   208.5  751.93   217.7752.8022   223.6  754.01   238.8  754.05
   250.5  761.83   257.3  764.74   283.2  770.91   370.8  784.26   390.5  792.29
   403.6   800.4   416.7     810   436.4  821.62   446.3  825.89   470.3  831.27
#Mann= 3 ,-1,0
       0      .1       0   197.3    .045       0   217.7      .1       0
Bank Sta=197.3,217.7
XS Rating Curve= 0 ,0
Exp/Cntr(USF)=0,0
Exp/Cntr=0.3,0.1

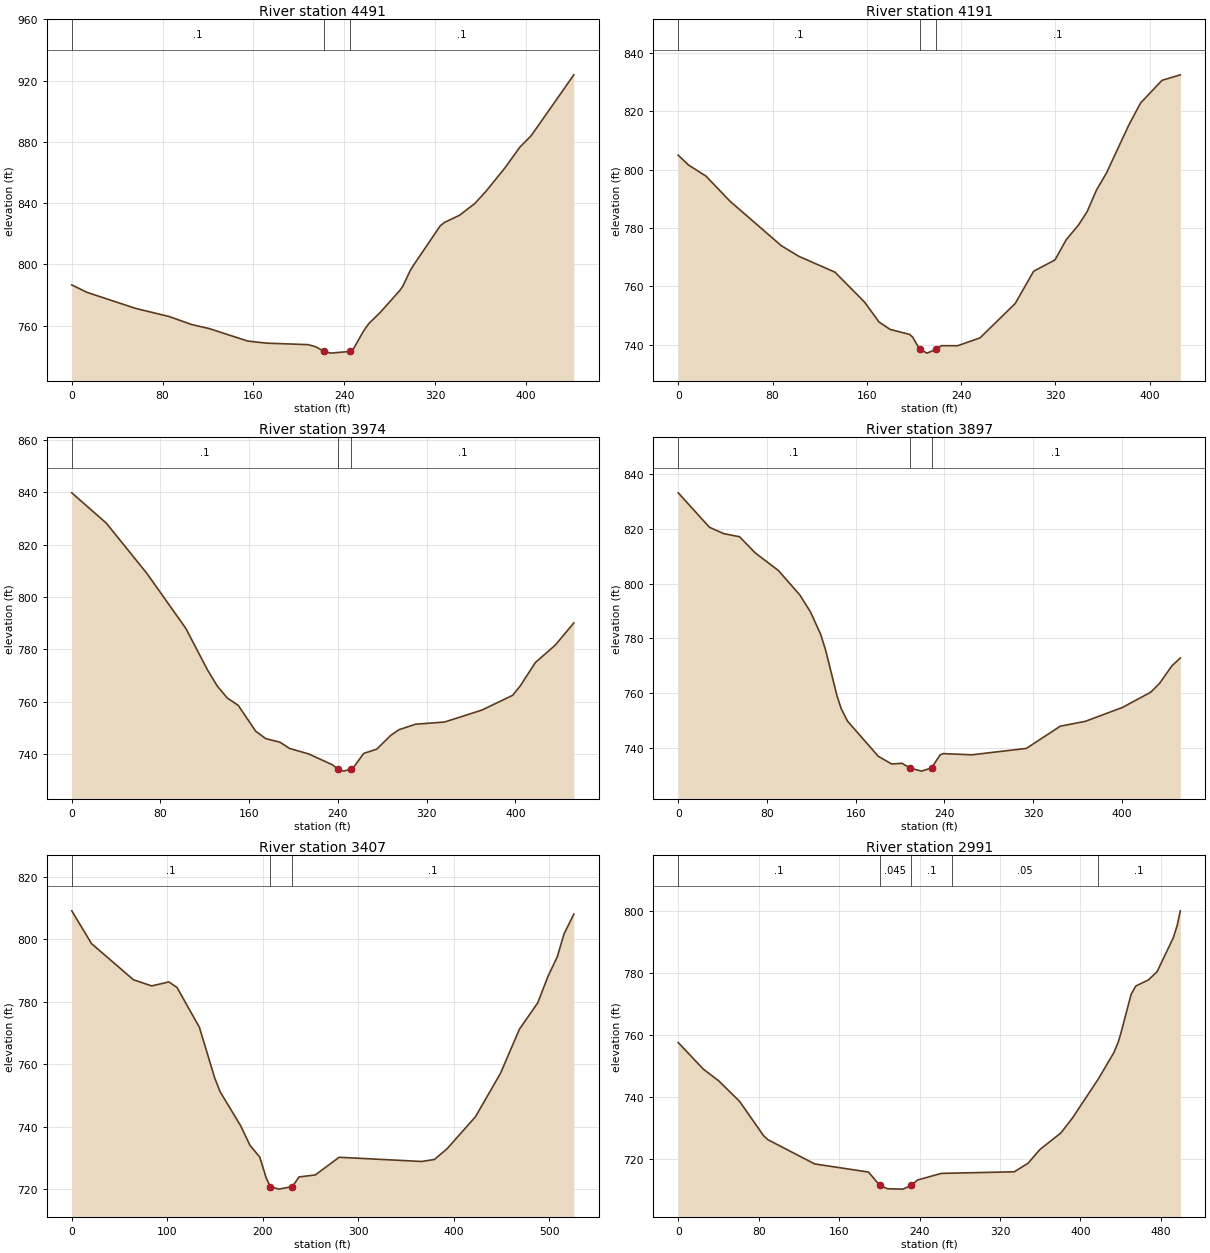
Type RM Length L Ch R = 1 ,4491    ,293.5,300,312.3
XS GIS Cut Line= 6
1627571.20666784473517.3754415071627562.62564826473621.411322668
1627568.46881242473696.5391251741627587.18006109473794.772852585
1627600.37327617473868.6083348391627613.63538876473955.155405834
#Sta/Elev= 30
       0  786.64    13.5  781.76    56.3   771.3    85.9  765.98   105.7  760.75
   120.9  758.17     155     750   171.5  748.62   208.1  747.66   214.7  746.32
   222.4743.2288   228.1  742.11   245.5743.2512   248.2  744.98   256.8  756.21
   261.5  761.23   271.6  768.57     289  783.01   291.6  785.78   298.2  796.08
   301.1  799.55   324.5   825.1   328.2  827.38   341.6  832.12   354.9  839.67
   364.9  847.75   381.5  862.93   394.7  876.53   404.7  884.02   442.3  923.77
#Mann= 3 ,-1,0
       0      .1       0   222.4    .045       0   245.5      .1       0
Bank Sta=222.4,245.5
XS Rating Curve= 0 ,0
Exp/Cntr(USF)=0,0
Exp/Cntr=0.3,0.1

Type RM Length L Ch R = 1 ,4191    ,213.5,217.1,216.4
XS GIS Cut Line= 6
1627466.38076201473429.7949080021627414.41793942473500.194373503
1627369.87734608473560.5361163321627310.49196617473640.993304506
1627261.37920351473697.9607102571627200.35767201473761.847721592
#Sta/Elev= 30
       0  804.99     8.7  801.62    23.6  797.79      44  789.17    87.5  773.93
   102.5  770.26     133  764.86   158.2  754.56   170.4  747.76   179.9   745.2
   196.4   743.5     199  742.54   204.9738.4111   211.2  737.08   218.9738.3873
   223.4  739.64     237  739.61   256.1   742.3     286  754.12   301.6  765.16
   319.7  769.05   329.3  775.99   339.7  781.04   347.1  785.69   355.1  793.15
   363.4  798.84   382.4  815.33   392.4   822.9   410.6  830.67   426.1  832.55
#Mann= 3 ,-1,0
       0      .1       0   204.9    .045       0   218.9      .1       0
Bank Sta=204.9,218.9
XS Rating Curve= 0 ,0
Exp/Cntr(USF)=0,0
Exp/Cntr=0.3,0.1

Type RM Length L Ch R = 1 ,3974    ,74.8,76.9,74.2
XS GIS Cut Line= 3
1627352.34165541473317.4409248671627113.40855706473525.419127889
1627075.68227837473656.010092577
#Sta/Elev= 30
       0   839.8    31.1  828.24    67.9  808.93   102.8  788.05   122.4  772.15
   131.1  766.07   140.1  761.48   150.1  758.61   165.9  748.72   174.8  745.94
   187.7  744.55   196.4  742.17   213.8  740.04   235.1   735.9   240.1  734.27
   245.1   733.5   251.6  734.26   255.1  735.51   263.2  740.26     275   741.9
   287.7  747.19     295  749.31     310  751.42   336.1  752.25   369.7   756.8
   397.5  762.45   404.4  766.06     418  774.98   435.9  781.61   452.7  790.11
#Mann= 3 ,-1,0
       0      .1       0   240.1    .045       0   251.6      .1       0
Bank Sta=240.1,251.6
XS Rating Curve= 0 ,0
Exp/Cntr(USF)=0,0
Exp/Cntr=0.3,0.1

Type RM Length L Ch R = 1 ,3897    ,491.4,490.4,476.8
XS GIS Cut Line= 6
1627306.73180309473294.7725402561627232.81003493473341.589375749
1627169.44828501473381.7179044191627088.91859043473447.507799089
1627044.13751201473522.2842243461626997.61759192473609.729915589
#Sta/Elev= 30
       0  833.24    28.1  820.66    40.9  818.33    55.3  817.18    69.4  811.28
    90.3  804.84   109.7  795.87   119.3  789.65   128.5  781.41     133  775.56
   143.1  759.09   146.9  754.35   152.6  749.77   180.4  736.89   192.5  734.08
   201.8  734.33   208.8  732.64   219.3  731.47   228.4  732.64   236.2  737.44
   239.1  737.87   264.7  737.44   313.9  739.78   344.5  747.91     367  749.67
   400.5  754.75     426  760.32   433.9  763.52   445.1  769.96   452.7  772.84
#Mann= 3 ,-1,0
       0      .1       0   208.8    .045       0   228.4      .1       0
Bank Sta=208.8,228.4
XS Rating Curve= 0 ,0
Exp/Cntr(USF)=0,0
Exp/Cntr=0.3,0.1

Type RM Length L Ch R = 1 ,3407    ,410.4,415.7,418.2
XS GIS Cut Line= 6
1626712.66759784473116.6920043371626699.43468467 473204.49727492
1626686.07447516473278.6532945921626657.30550384473451.272371917
1626649.32434383473500.9830098031626664.41126878473636.677356802
#Sta/Elev= 30
       0  809.17    20.7  798.67    64.6  787.11    83.7  785.14   101.8   786.4
   110.3  784.62   133.7  771.89   149.8  755.62   155.5  751.21     177  740.33
   186.7  734.11     197  730.31   203.6  723.73   207.9720.8967   216.9  720.08
   231.1 720.903   238.1  723.98   255.2  724.63   280.1  730.28   366.5  728.93
   379.9  729.57   393.1  732.98   422.9  743.24   449.2  757.18     469  771.29
   488.2  779.72   498.8  788.11   508.7  794.48   515.6  801.69     526  808.12
#Mann= 3 ,-1,0
       0      .1       0   207.9    .045       0   231.1      .1       0
Bank Sta=207.9,231.1
XS Rating Curve= 0 ,0
Exp/Cntr(USF)=0,0
Exp/Cntr=0.3,0.1

Type RM Length L Ch R = 1 ,2991    ,329,337.6,340.9
XS GIS Cut Line= 6
1626442.80177243    472935.173851626398.08302984473010.383345261
1626359.75239784473074.8487675041626308.64488851473160.802335754
1626270.31392843473225.2674299181626146.52050499473329.450937144
#Sta/Elev= 30
       0  757.58      25  749.02    40.3  745.26      61  738.68    84.9  727.62
    89.3  726.34   135.7  718.57   189.2  715.96   200.4 711.665   208.2  710.59
   223.5  710.47   231.5711.6534   238.1  713.41   261.7  715.53   334.2  716.04
   347.9  718.79   359.6  723.18   380.5  728.51   392.2   733.4   417.8  745.89
   433.3  754.38   437.6  757.74   440.1  760.46   450.4  773.08     455  775.73
   467.6  777.71   476.2  780.35   492.3  791.24   496.2  795.21   499.3  799.91
#Mann= 5 ,-1,0
       0      .1       0   200.4    .045       0   231.5      .1       0
   272.5     .05       0   417.5      .1       0
Bank Sta=200.4,231.5
XS Rating Curve= 0 ,0
Exp/Cntr(USF)=0,0
Exp/Cntr=0.3,0.1

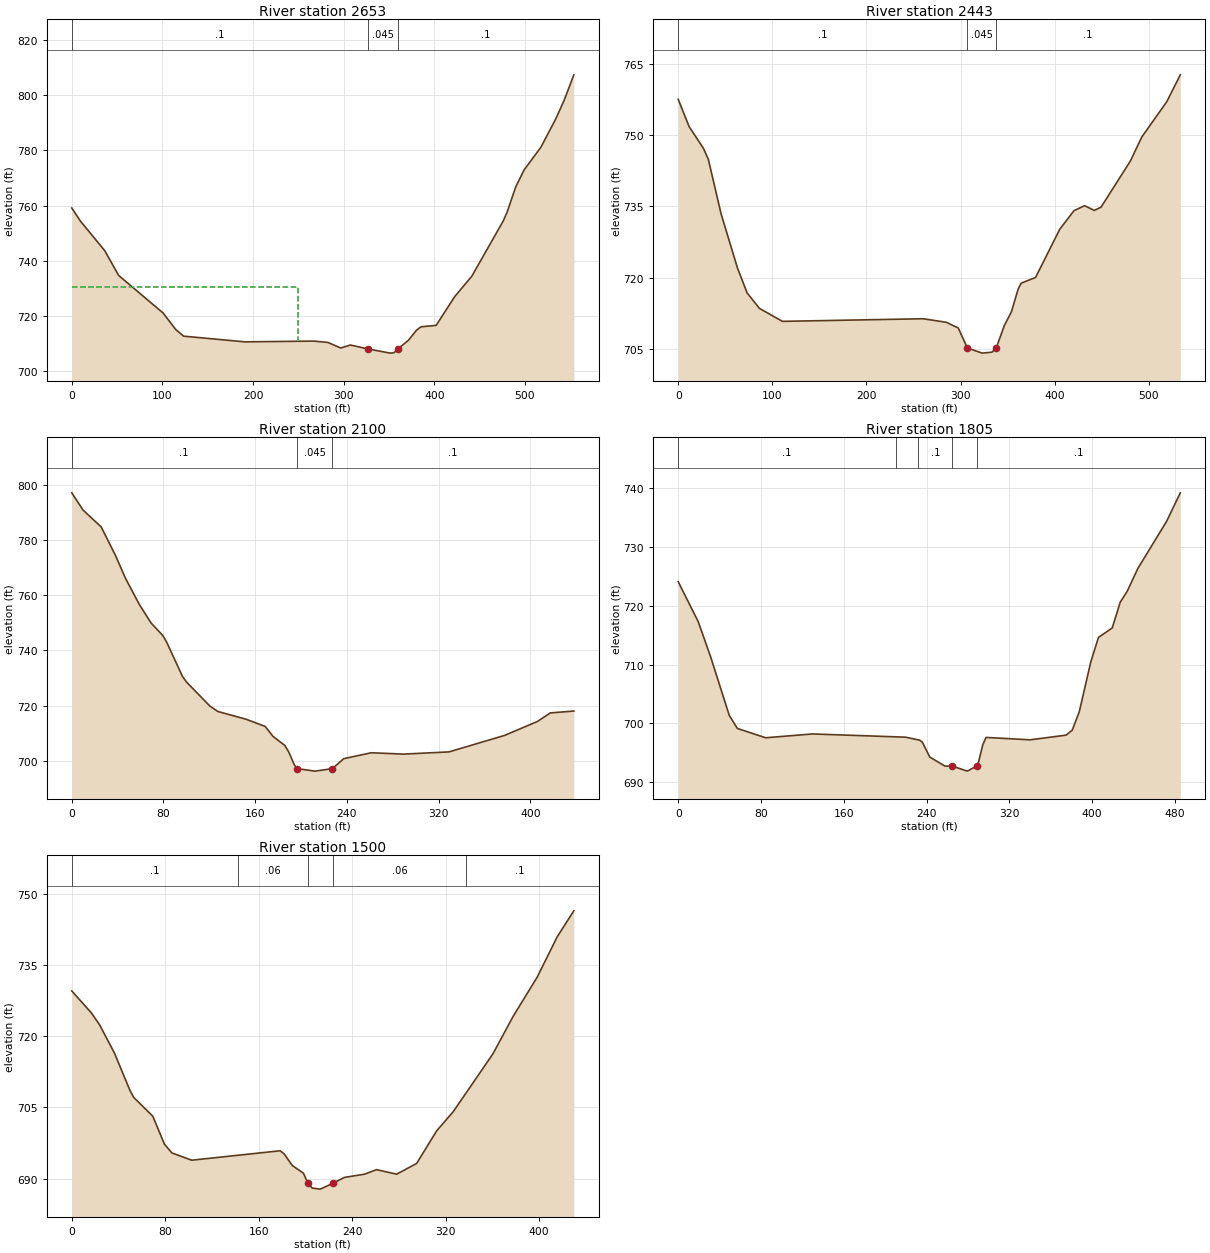
Type RM Length L Ch R = 1 ,2653    ,203.3,209.9,214.2
XS GIS Cut Line= 3
1626309.31440922 472743.588438461625995.04835127472998.042112387
1625889.02753724473103.559278354
#Sta/Elev= 30
       0  759.13     9.7  754.31    36.3   743.7    51.7  734.69   100.7  721.07
   114.9     715   123.4  712.66   190.9   710.6   266.9  710.87   282.7  710.38
   296.7  708.36   307.4  709.46   326.6 708.035   351.3  706.51   355.5  706.66
   359.9 708.064   371.3  711.14   380.4  714.84   385.3  716.06     402  716.57
   422.5  727.02   441.4  734.42     476  754.42   480.4  757.73   489.8  766.79
   499.2  773.02   517.5  781.13   533.9  791.37   543.2  798.16   553.9   807.4
#Mann= 3 ,-1,0
       0      .1       0   326.6    .045       0   359.9      .1       0
#XS Ineff= 2 , 0
          249.83  730.64
Permanent Ineff=
       F       F
Bank Sta=326.6,359.9
XS Rating Curve= 0 ,0
Exp/Cntr(USF)=0,0
Exp/Cntr=0.3,0.1

Type RM Length L Ch R = 1 ,2443    ,342.1,343.3,343.5
XS GIS Cut Line= 4
1626232.12404997472647.603868476 1626171.7559283472697.474150678
 1625888.7966421472797.7635179391625754.94039758472875.798256731
#Sta/Elev= 30
       0  757.48    11.5  751.76    26.8  747.15      32  744.84    45.5  733.42
    62.9  722.03    73.2  716.76    86.3  713.51   110.7  710.78   260.3  711.33
   284.7  710.59   297.5   709.4   307.3705.1736     323   704.1   333.4  704.31
   337.8705.1317   346.4  709.84   354.1  712.83   361.3  717.64   364.4  718.81
   379.7  720.01   405.3  730.11   420.5  734.06   431.9   735.1   442.1  734.11
   449.3   734.8   480.4  744.48   492.6  749.55   519.2     757   533.5  762.62
#Mann= 3 ,-1,0
       0      .1       0   307.3    .045       0   337.8      .1       0
Bank Sta=307.3,337.8
XS Rating Curve= 0 ,0
Exp/Cntr(USF)=0,0
Exp/Cntr=0.3,0.1

Type RM Length L Ch R = 1 ,2100    ,307.9,294.6,281.2
XS GIS Cut Line= 6
1626049.94396234472390.3799920831625966.26335542 472415.94916667
1625894.53679284472437.8651333451625798.90181351472467.086859673
1625732.68967558472506.9657169281625660.74100059472573.593208343
#Sta/Elev= 30
       0  797.06     9.9  790.79    25.7   784.7    38.3  774.24    46.7  766.24
    58.9  756.66    69.2  749.92    79.5  745.35    82.9  742.88    96.6  730.57
   100.1  728.55   120.6   719.8   127.5  717.88   151.8  715.12   168.7  712.49
   175.5  708.89   185.8   705.6   189.3  703.21   193.9  698.78   196.2697.2125
   212.3   696.3   227.2 697.198   237.3  700.82   261.3  702.95   289.4  702.46
   329.1  703.27   377.7  709.26   406.1  714.27   417.4  717.38   437.9  718.05
#Mann= 3 ,-1,0
       0      .1       0   196.2    .045       0   227.2      .1       0
Bank Sta=196.2,227.2
XS Rating Curve= 0 ,0
Exp/Cntr(USF)=0,0
Exp/Cntr=0.3,0.1

Type RM Length L Ch R = 1 ,1805    ,291.4,305.4,324.6
XS GIS Cut Line= 6
1625805.29714192472155.5133358391625704.64445609 472221.01254867
1625627.66462317472288.1393829291625584.93603408472379.188413426
 1625560.5167916 472450.101657421625532.02800342 472532.83410351
#Sta/Elev= 30
       0  724.07    19.3   717.3    31.3  711.32    49.3  701.37    57.1  699.14
    84.5  697.55   129.8   698.2   219.9  697.65   233.5  697.13   235.9  696.81
   243.2  694.26   257.7  692.74   264.9  692.74   279.5  691.88  288.41692.7422
   290.3  693.44   294.3  696.32   297.5  697.61   340.2   697.2   374.9     698
   380.8  698.84   387.6  701.94   398.8  710.46   406.2  714.61   419.5  716.22
   427.2  720.59   433.9  722.43   444.3  726.34   472.1  734.36   485.3  739.19
#Mann= 5 ,-1,0
       0      .1       0  210.09     .06       0  232.22      .1       0
   264.9    .045       0  288.41      .1       0
Bank Sta=264.9,288.41
XS Rating Curve= 0 ,0
Exp/Cntr(USF)=0,0
Exp/Cntr=0.3,0.1

Type RM Length L Ch R = 1 ,1500    ,306.8,299.8,290.6
XS GIS Cut Line= 6
1625813.65998609472092.6952200081625721.36981633472095.376973167
1625649.80532692472072.9373854991625554.38622643 472043.01815401
1625482.82173701472020.5785663431625399.33010609 471994.39882867
#Sta/Elev= 30
       0  729.56    16.9  724.88    23.9  722.38    36.6  716.42    49.7  708.64
      53  707.11    69.4  703.13    79.3  697.25    85.8  695.38   102.7  693.86
   178.3  695.85   181.8   695.2   188.7  692.76   198.3  691.12   202.2688.9833
   205.8  687.99   212.7  687.76   223.7689.0061   233.4  690.23   250.6  690.91
   260.9  691.87   278.1  690.91   295.2  693.17   312.4  700.06   326.6  704.11
   360.6  716.32   377.8  724.18   398.4  732.45   415.6  740.99   429.8  746.45
#Mann= 5 ,-1,0
       0      .1       0  142.33     .06       0   202.2    .045       0
   223.7     .06       0  337.33      .1       0
Bank Sta=202.2,223.7
XS Rating Curve= 0 ,0
Exp/Cntr(USF)=0,0
Exp/Cntr=0.3,0.1