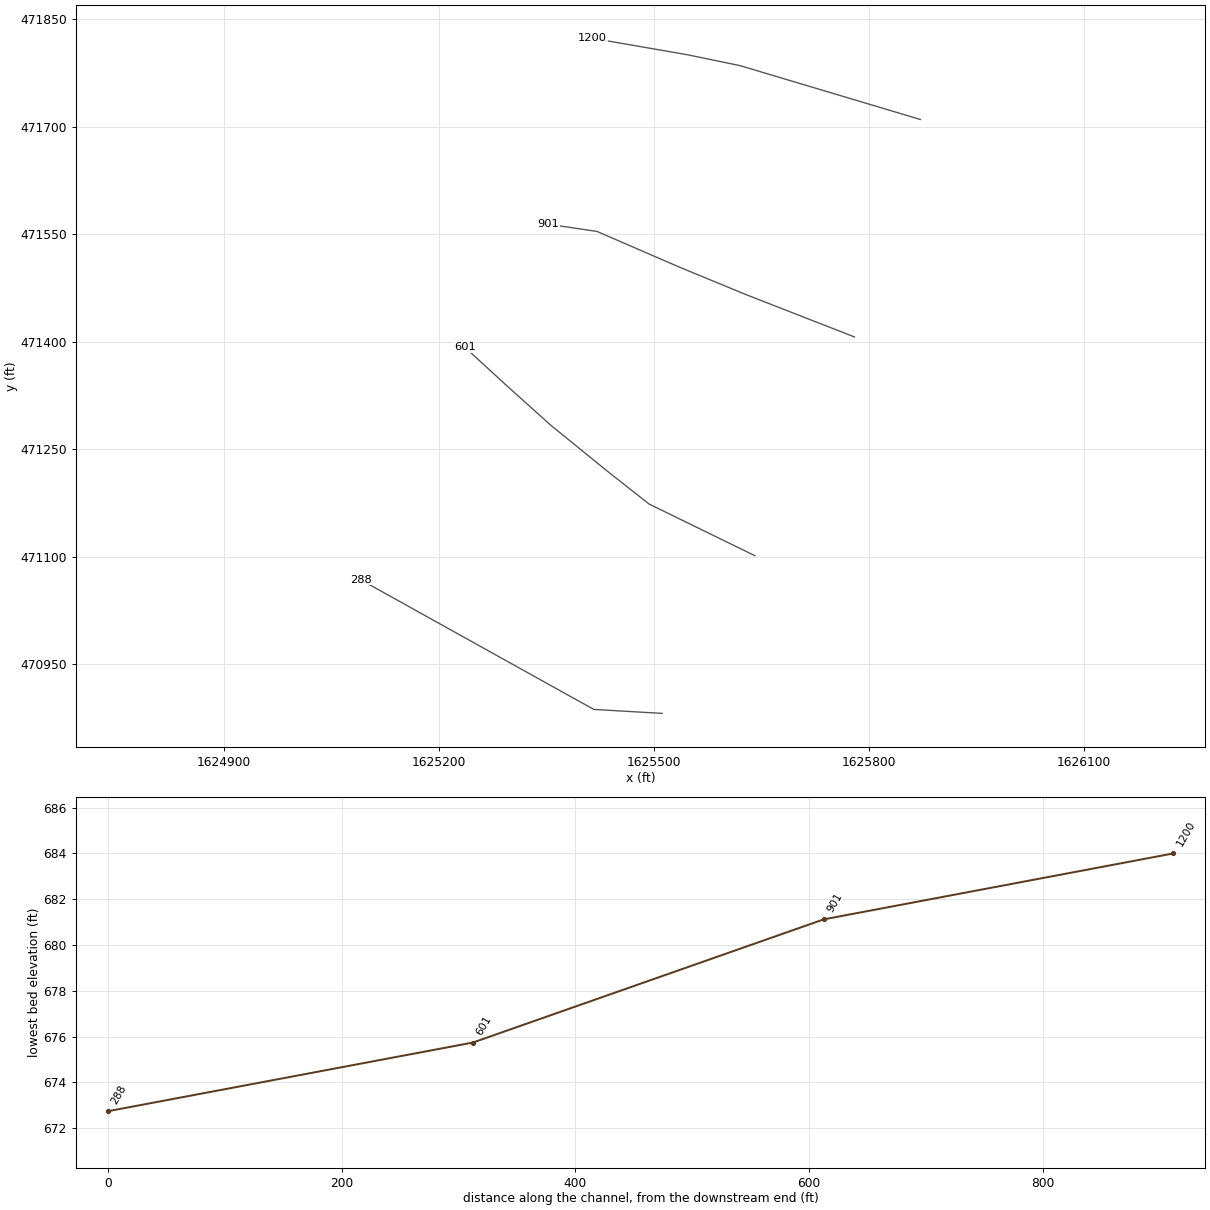
HEC-RAS study LwrBwmRn.prj: LwrBwmRn

--- LwrBwmRn.g01 (geometry) --- (continued)

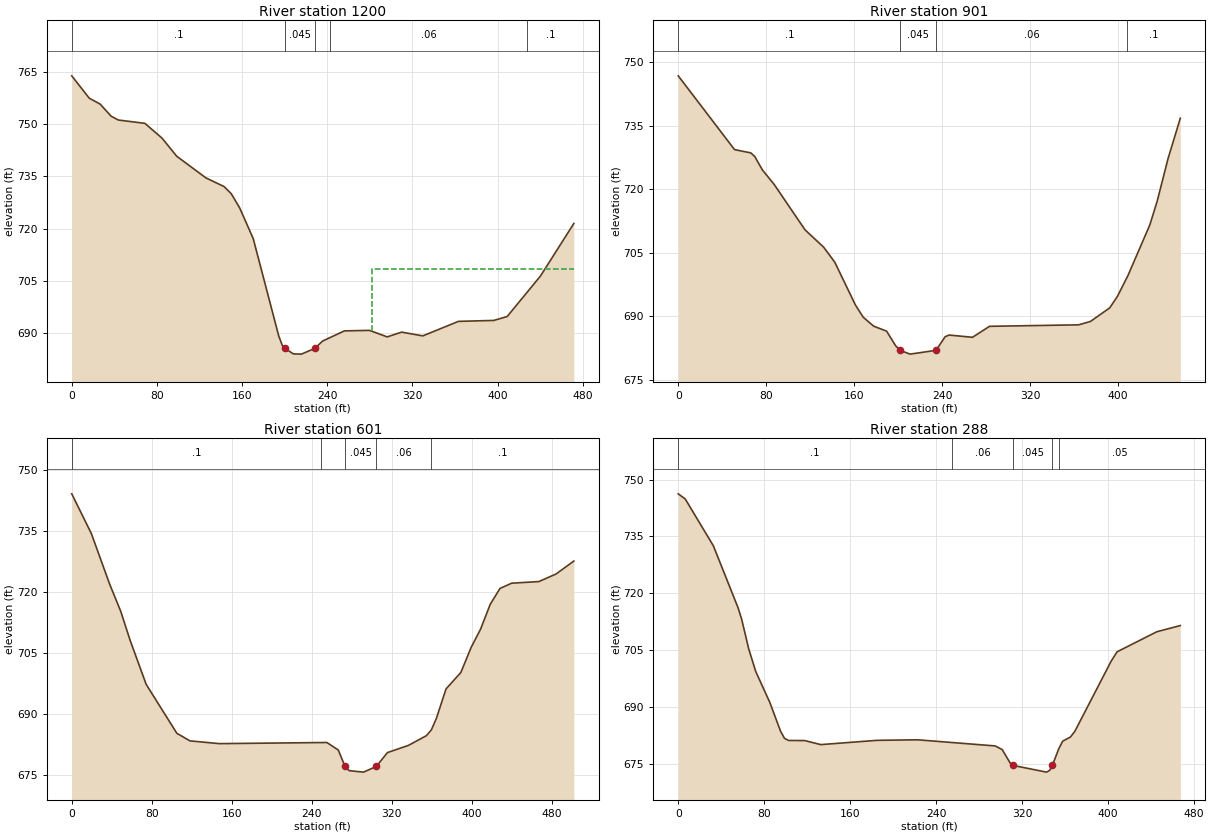
Type RM Length L Ch R = 1 ,1200    ,300.2,299.2,297
XS GIS Cut Line= 6
 1625871.5670225471709.9748568391625787.66167851471735.075856507
 1625715.7248145471756.5197112561625619.89167283471785.158433512
1625546.33309293471800.3388493361625414.32750728471823.211237674
#Sta/Elev= 30
       0  763.78    16.4  757.38    26.7  755.67      37   752.2    43.8  751.11
    68.7  750.16    84.9  745.89    98.6  740.73     126  734.53   143.1  732.03
   149.8     730   157.7  725.95   170.5   717.1   194.5  689.15   197.9  686.44
   200.4685.6364   208.2  684.07   215.7     684   228.4685.6462   235.6  687.74
   256.1  690.66   279.7  690.81   296.4  688.94   309.9  690.31   329.8  689.23
   363.3  693.39   396.6  693.66   409.1  694.79   440.3  706.37   471.7  721.45
#Mann= 5 ,-1,0
       0      .1       0   200.4    .045       0   228.4      .1       0
  242.64     .06       0  427.77      .1       0
#XS Ineff= 2 , 0
                          282.36          708.43
Permanent Ineff=
       F       F
Bank Sta=200.4,228.4
XS Rating Curve= 0 ,0
Exp/Cntr(USF)=0,0
Exp/Cntr=0.3,0.1

Type RM Length L Ch R = 1 ,901     ,302.9,300.2,293.4
XS GIS Cut Line= 6
1625779.55900443  471406.6552535 1625698.0460441471438.465229258
1625628.17774551 471465.730594681625535.71959709 471503.87815617
1625420.36479362471553.8164094641625352.69100004471563.940165699
#Sta/Elev= 30
       0  746.76    51.2  729.36      66  728.58    69.6  727.73    76.6  724.54
    87.2  721.16   115.3  710.44   132.3  706.33   142.4  702.79   161.1  692.73
   168.2  689.83   177.7  687.72   189.5  686.54   197.8  683.06   202.1 681.988
   210.8  681.12   234.4682.0095   242.7  685.21   246.3  685.62   267.6  685.09
   283.1  687.68   364.2  688.03   374.9  688.83   392.4  692.03   399.4  694.74
     409  699.66   428.9  711.61   435.6  717.22   445.4  727.19   456.6  736.77
#Mann= 4 ,-1,0
       0      .1       0   202.1    .045       0   234.4     .06       0
  408.22      .1       0
Bank Sta=202.1,234.4
XS Rating Curve= 0 ,0
Exp/Cntr(USF)=0,0
Exp/Cntr=0.3,0.1

Type RM Length L Ch R = 1 ,601     ,309.2,312.4,315.3
XS GIS Cut Line= 6
1625640.54687691471101.4852014291625493.01758276  471173.5454835
1625434.10595517471219.9610730861625356.46634668471283.002613679
1625300.51403075471333.1744293421625235.76809725471392.383300424
#Sta/Elev= 30
       0  744.22    19.6  734.43    37.9  721.99    48.9  715.35    58.5  708.08
    74.4  697.34   105.1  685.29   118.2  683.43   147.4  682.75   255.1  683.03
   266.5  681.19   273.3677.1367   277.5  676.09   291.8  675.74   304.6677.1463
   315.7  680.55   336.7  682.32   354.7  684.72   359.6  686.13   364.6  688.94
   374.3  696.22   389.1  700.26   399.5  706.48   408.8   710.9   418.5  717.04
   428.2  720.93   439.9  722.23   467.1  722.63   484.3  724.49   502.1  727.68
#Mann= 5 ,-1,0
       0      .1       0  249.19     .06       0   273.3    .045       0
   304.6     .06       0   359.2      .1       0
Bank Sta=273.3,304.6
XS Rating Curve= 0 ,0
Exp/Cntr(USF)=0,0
Exp/Cntr=0.3,0.1

Type RM Length L Ch R = 1 ,288     ,,,
XS GIS Cut Line= 6
1625511.22658604470881.4805396551625416.11852715470886.972795158
1625385.80878478470903.7169334111625232.87470745470988.782380071
1625167.33120337471025.239000079 1625090.8641647471067.771723401
#Sta/Elev= 30
       0  746.26     6.5  744.91    32.7  732.53    55.7  716.16      59  713.19
    65.6  705.32    72.2  699.29    85.3  691.13    95.2  683.58    98.9  681.67
   102.7   681.1   117.7  681.08   132.7  680.01   185.2  681.14   222.8  681.28
   295.1  679.66   301.6  678.69   309.1   675.1   311.7 674.512   342.9  672.74
   345.8  673.22   348.3674.5118   354.2  678.87   357.9  680.92   365.1  682.01
   369.2  683.51     403  702.04   408.5  704.52   445.5  709.82   467.4  711.46
#Mann= 5 ,-1,0
       0      .1       0  254.89     .06       0   311.7    .045       0
   348.3     .06       0  354.89     .05       0
Bank Sta=311.7,348.3
XS Rating Curve= 0 ,0
Exp/Cntr(USF)=0,0
Exp/Cntr=0.3,0.1
LCMann Table=0

Chan Stop Cuts=-1
Use User Specified Reach Order=0
Composite Channel Slope=5